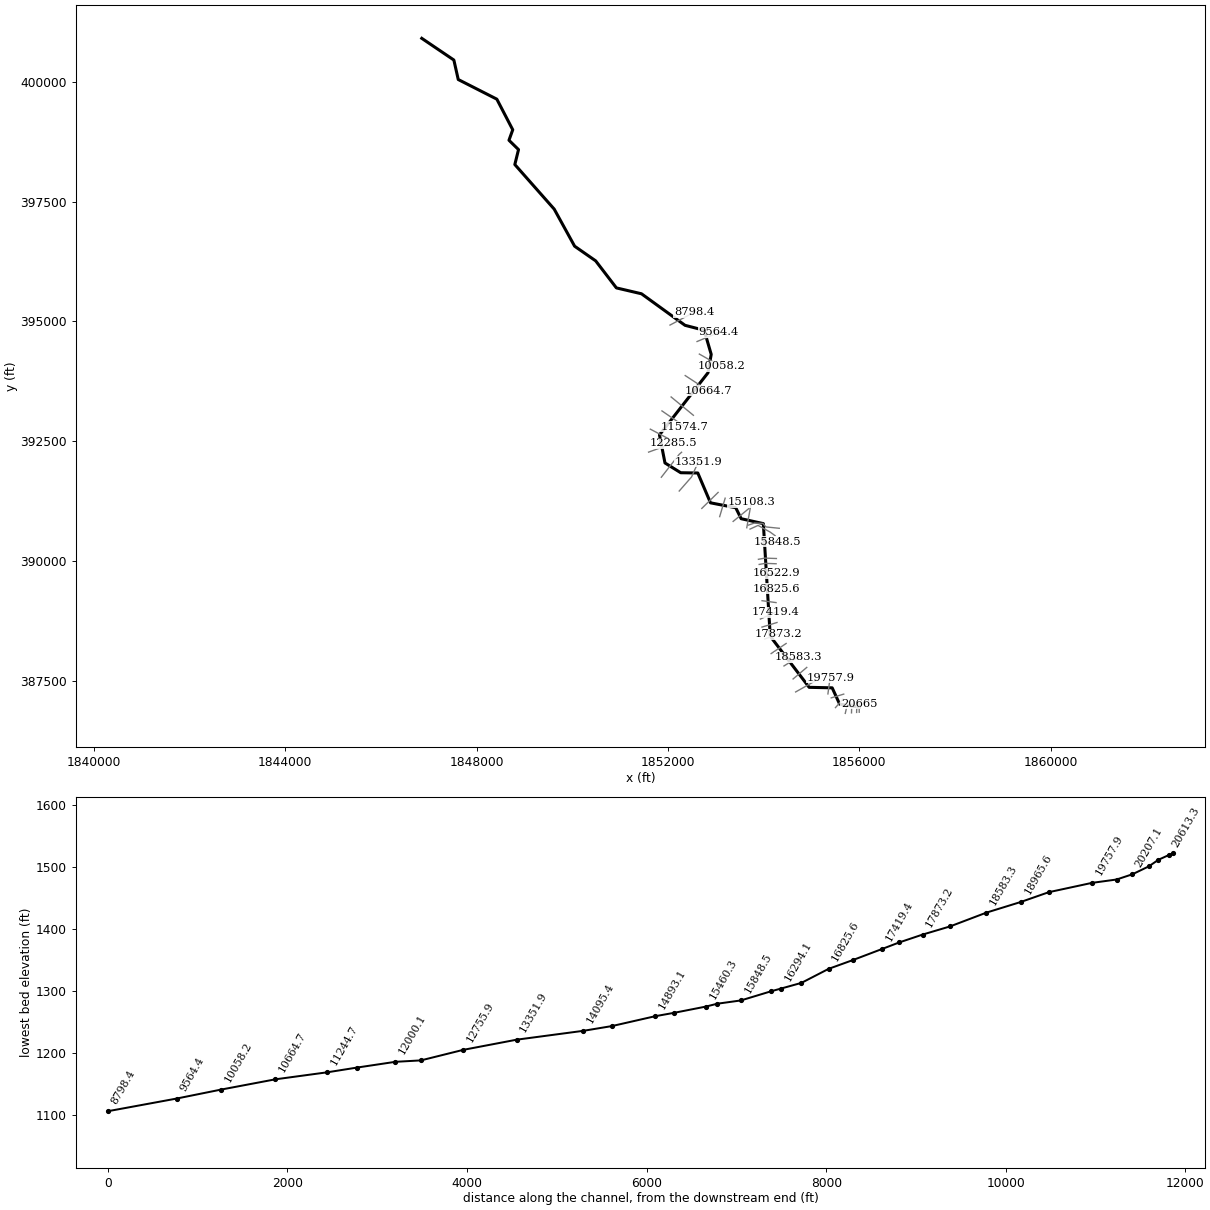
--- AaronCk.prj (project) ---

Proj Title=AaronCk
Current Plan=p01
Default Exp/Contr=0,0
English Units
Geom File=g01
Flow File=f01
Plan File=p01
BEGIN DESCRIPTION:
END DESCRIPTION:
DSS Export Rating Curves= 0
DSS Export Rating Curve Sorted= 0
DSS Export Volume Flow Curves= 0
DXF Filename=m:\Didavi\Junko\AaronCk.
DXF OffsetX= 0
DXF OffsetY= 0
DXF ScaleX= 0
DXF ScaleY= 0

--- AaronCk.p01 (plan) ---

Plan Title=Floodplain
Program Version=4.00
Geom File=g01
Flow File=f01
K Sum by GR=0
Std Step Tol=0.01
Critical Tol=0.01
Num of Std Step Trials=20
Max Error Tol=0.3
Flow Tol Ratio=0.001
Split Flow NTrial=30
Split Flow Tol=0.02
Split Flow Ratio=0.02
Log Output Level=0
Friction Slope Method=1
Unsteady Friction Slope Method=2
Unsteady Bridges Friction Slope Method=1
Global Log Level=0
CheckData=False
Run HTab=0
Run UNet=0
Run PostProcess=0
UNET Theta=0
UNET Theta Warmup=0
UNET ZTol=0
UNET ZSATol=0
UNET MxIter=0
UNET MaxInSteps=0
UNET DtIC=0
UNET DtMin=0
UNET MaxCRTS=0
UNET WFStab=0
UNET SFStab=0
UNET WFX=0
UNET SFX=0
UNET DSS MLevel=0
UNET DZMax Abort=0
UNET Convert EG Bridges=0
UNET Use Existing IB Tables=0
UNET Froude Limit=0
UNET Froude Power=0
Write IC File=0
Echo Input=False
Echo Output=False
Write Detailed=0

--- AaronCk.f01 (steady flow) ---

Flow Title=NFF Regression Equation
Program Version=4.10
Number of Profiles= 1
Profile Names=P100yr
River Rch & RM=AaronCk,Main            ,20665
     889
River Rch & RM=AaronCk,Main            ,19276.3
     910
River Rch & RM=AaronCk,Main            ,17873.2
     934
River Rch & RM=AaronCk,Main            ,16522.9
     989
River Rch & RM=AaronCk,Main            ,15584.6
    1007
River Rch & RM=AaronCk,Main            ,15108.3
    1260
River Rch & RM=AaronCk,Main            ,11574.7
    1340
River Rch & RM=AaronCk,Main            ,10058.2
    1385
River Rch & RM=AaronCk,Main            ,7360.5
    1455
River Rch & RM=AaronCk,Main            ,5132.2
    1541
River Rch & RM=AaronCk,Main            ,2655.9
    1615
River Rch & RM=AaronCk,Main            ,275.8
    1793
Boundary for River Rch & Prof#=AaronCk,Main            , 1
Up Type= 0
Dn Type= 1
Dn Known WS=944
DSS Import GetInterval= 0
DSS Import GetPeak= 0
DSS Import FillOption= 0

--- AaronCk.g01 (geometry) ---

Geom Title=USGS 10m DEM
Program Version=4.10

River Reach=AaronCk         ,Main
Reach XY= 30
     1856002.109      386950.982     1855588.262      387012.052
     1855432.339      387352.485     1854951.314       387362.88
     1854137.849      388428.082     1853993.166      390779.092
      1853529.31      390881.908     1853415.801      391111.162
     1852888.636      391213.173     1852622.715      391835.731
      1852265.86      391841.272     1851936.591      392045.223
     1851821.648      392631.611      1852835.98      393926.994
     1852903.177      394311.082     1852756.403      394814.004
     1852355.929      394917.512     1851445.518      395575.578
     1850920.786      395698.184     1850487.656      396262.527
      1850047.57      396568.454      1849621.06       397341.89
     1848797.449      398272.619     1848874.706      398584.251
     1848675.053      398779.564     1848754.046      398997.966
     1848421.407      399636.855      1847614.55      400046.751
     1847522.883      400453.348      1846852.07      400906.177

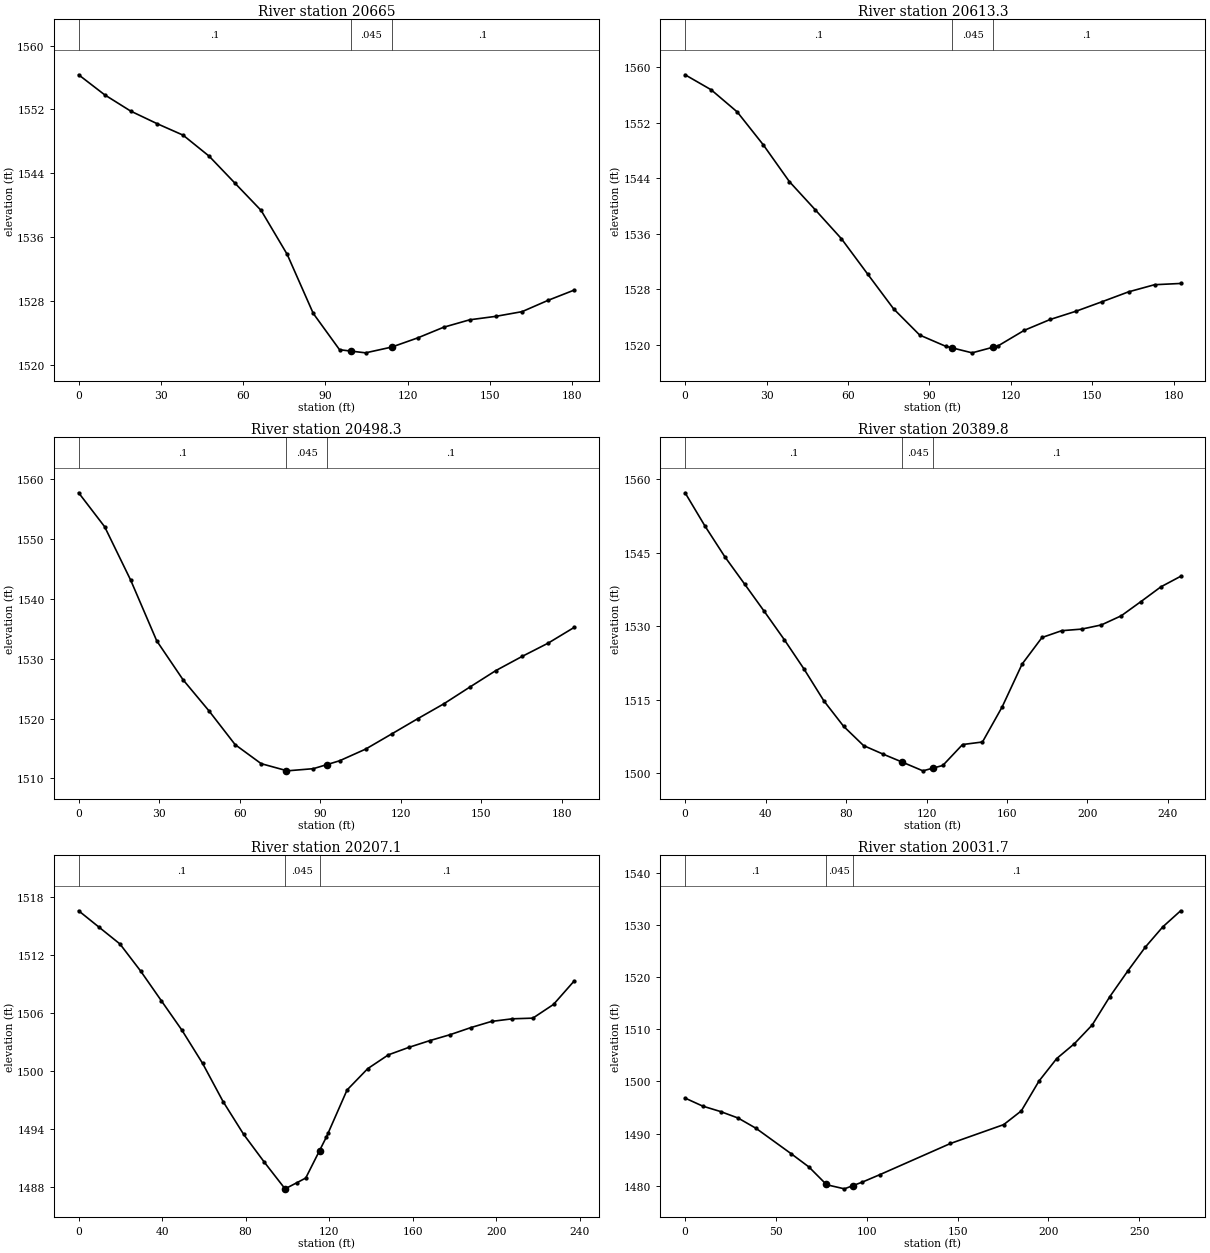
Type RM Length L Ch R = 1 ,20665   ,52.4,51.7,51
XS GIS Cut Line= 2
     1855997.954       386843.71     1855996.568        387024.5
#Sta/Elev= 23
       0 1556.34     9.5 1553.83      19 1551.79    28.6 1550.22    38.1 1548.78
    47.6 1546.15    57.1 1542.74    66.6 1539.34    76.1 1533.84    85.6 1526.45
    95.2  1521.9    99.21521.734    99.3 1521.73   104.7 1521.51   114.2 1522.23
   114.3 1522.24   123.7 1523.38   133.2 1524.72   142.7 1525.65   152.2 1526.08
   161.8 1526.67   171.3 1528.09   180.8 1529.37
#Mann= 3 , 0 , 0
       0      .1       0    99.2    .045       0   114.3      .1       0
Bank Sta=99.2,114.3
XS Rating Curve= 0 ,0
Exp/Cntr=0.3,0.1

Type RM Length L Ch R = 1 ,20613.3 ,115.2,115,114.8
XS GIS Cut Line= 2
     1855943.285      386839.154     1855947.432       387021.61
#Sta/Elev= 23
       0 1558.88     9.6 1556.72    19.2 1553.53    28.8 1548.79    38.4  1543.5
      48 1539.41    57.6 1535.26    67.2  1530.2    76.8 1525.17    86.4  1521.4
      96 1519.78    98.4 1519.55    98.5 1519.54   105.7 1518.84   113.5 1519.66
   115.3 1519.85   124.9 1522.08   134.5 1523.65   144.1 1524.85   153.7 1526.22
   163.3 1527.62   172.9 1528.65   182.5 1528.83
#Mann= 3 , 0 , 0
       0      .1       0    98.4    .045       0   113.5      .1       0
Bank Sta=98.4,113.5
XS Rating Curve= 0 ,0
Exp/Cntr=0.3,0.1

Type RM Length L Ch R = 1 ,20498.3 ,113.1,108.5,104.2
XS GIS Cut Line= 2
     1855836.499      386830.256     1855840.693      387014.792
#Sta/Elev= 22
       0 1557.75     9.7 1552.07    19.4 1543.14    29.1    1533    38.9  1526.5
    48.6 1521.28    58.3 1515.66      68 1512.48    77.4 1511.32    77.7 1511.28
    87.4 1511.64    92.4 1512.31    97.2 1512.96   106.9 1514.91   116.6 1517.44
   126.3 1519.99     136 1522.47   145.7 1525.27   155.4 1528.03   165.2  1530.4
   174.9 1532.62   184.6 1535.25
#Mann= 3 , 0 , 0
       0      .1       0    77.4    .045       0    92.4      .1       0
Bank Sta=77.4,92.4
XS Rating Curve= 0 ,0
Exp/Cntr=0.3,0.1

Type RM Length L Ch R = 1 ,20389.8 ,194,182.8,171.3
XS GIS Cut Line= 2
     1855706.112       386819.39     1855761.024      387059.519
#Sta/Elev= 29
       0  1557.2     9.8 1550.47    19.7 1544.19    29.6 1538.58    39.4    1533
    49.3 1527.26    59.1 1521.28      69 1514.77    78.8 1509.59    88.7 1505.67
    98.5 1503.91     1081502.287   108.1 1502.27   108.4 1502.22   118.2 1500.52
   123.1 1501.06   128.1 1501.62   137.9 1505.88   147.8  1506.4   157.6 1513.56
   167.5 1522.28   177.4  1527.7   187.2 1529.09   197.1 1529.41   206.9 1530.26
   216.8 1532.13   226.6 1535.03   236.5 1538.03   246.3 1540.17
#Mann= 3 , 0 , 0
       0      .1       0     108    .045       0   123.1      .1       0
Bank Sta=108,123.1
XS Rating Curve= 0 ,0
Exp/Cntr=0.3,0.1

Type RM Length L Ch R = 1 ,20207.1 ,188.5,175.4,162.1
XS GIS Cut Line= 2
     1855500.989      386939.362      1855657.42      387117.922
#Sta/Elev= 28
       0 1516.59     9.9 1514.87    19.8 1513.15    29.7 1510.35    39.6 1507.28
    49.5 1504.22    59.4 1500.78    69.2 1496.83    79.1 1493.42      89 1490.54
    98.9 1487.79   104.6 1488.43   108.8 1488.91   115.41491.743   118.7 1493.16
   119.6  1493.6   128.6 1498.03   138.5 1500.24   148.4 1501.67   158.3 1502.45
   168.2 1503.14     178 1503.76   187.9 1504.49   197.8 1505.13   207.7  1505.4
   217.6 1505.47   227.5 1506.89   237.4 1509.32
#Mann= 3 , 0 , 0
       0      .1       0    98.9    .045       0   115.4      .1       0
Bank Sta=98.9,115.4
XS Rating Curve= 0 ,0
Exp/Cntr=0.3,0.1

Type RM Length L Ch R = 1 ,20031.7 ,247.6,273.8,300
XS GIS Cut Line= 2
     1855412.349      387142.949     1855673.595      387221.446
#Sta/Elev= 25
       0 1496.81     9.7 1495.27    19.5 1494.23    29.2 1492.98      39 1491.02
    58.4 1486.13    68.2 1483.58    77.4 1480.36    77.9 1480.18    87.7 1479.39
    92.51480.023    97.4 1480.66   107.2 1482.11   146.1  1488.1   175.4 1491.72
   185.1 1494.36   194.8 1500.07   204.6 1504.41   214.3 1507.25   224.1 1510.84
   233.8 1516.28   243.6 1521.16   253.3 1525.77     263 1529.69   272.8 1532.77
#Mann= 3 , 0 , 0
       0      .1       0    77.4    .045       0    92.5      .1       0
Bank Sta=77.4,92.5
XS Rating Curve= 0 ,0
Exp/Cntr=0.3,0.1

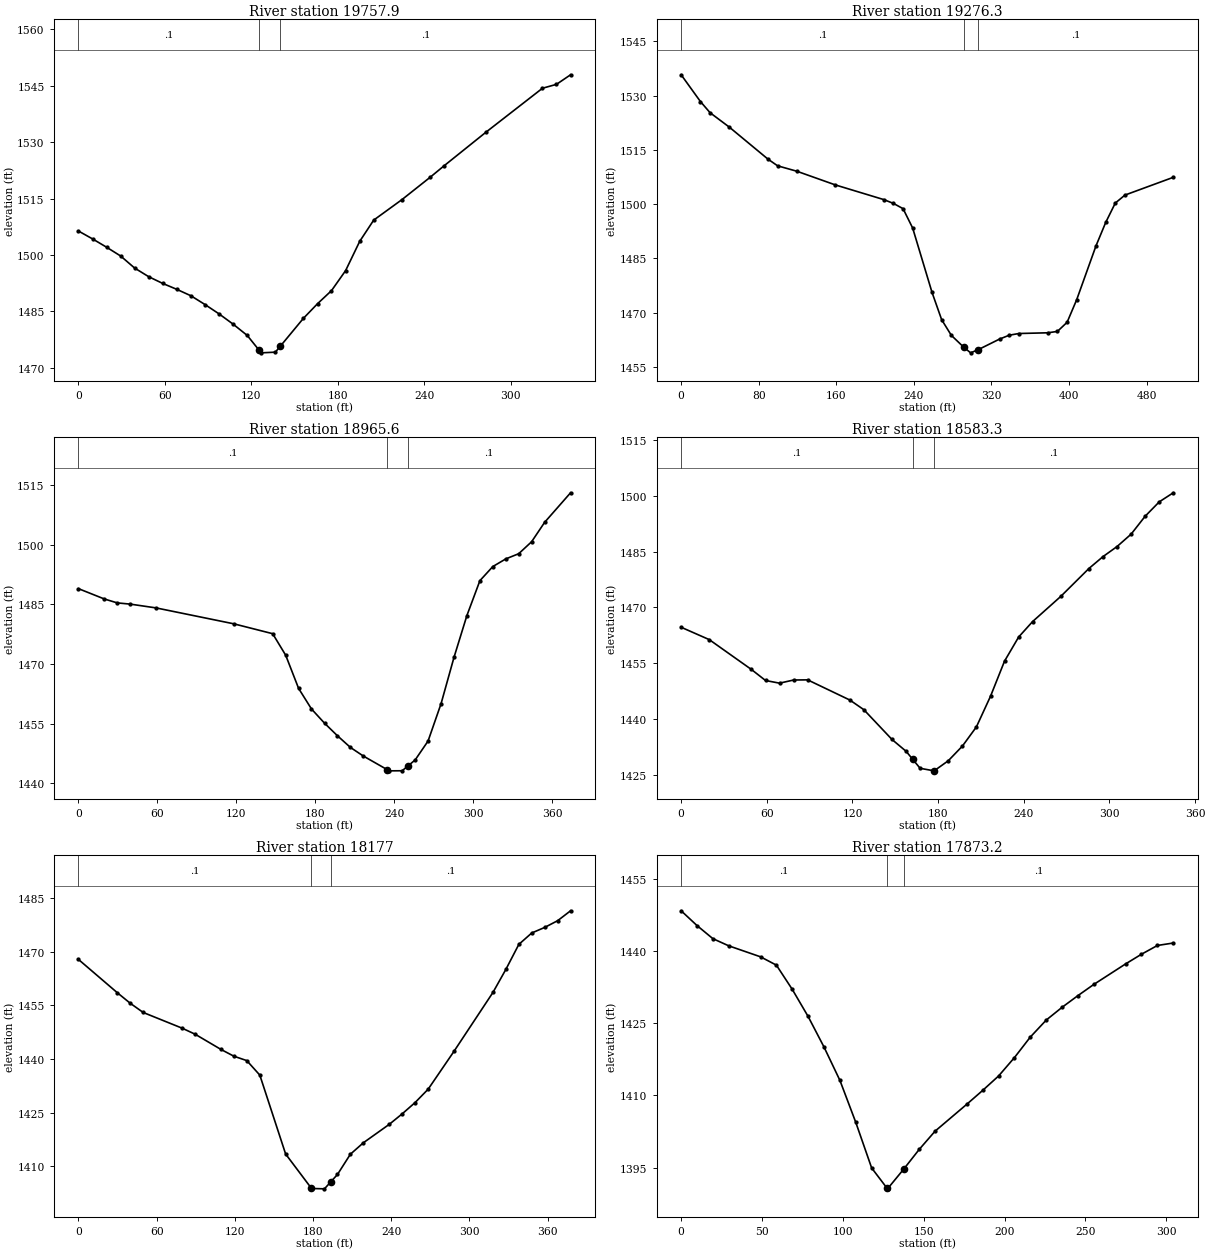
Type RM Length L Ch R = 1 ,19757.9 ,503.4,481.6,459.8
XS GIS Cut Line= 2
     1855343.159      387225.446     1855388.675      387564.102
#Sta/Elev= 30
       0 1506.38     9.8 1504.28    19.5 1502.08    29.3 1499.73      39 1496.53
    48.8 1494.22    58.6 1492.42    68.3 1490.86    78.1 1489.15    87.9 1486.81
    97.6 1484.34   107.4  1481.6   117.2  1478.6   125.1 1474.83   126.9 1473.97
   136.7 1474.15   140.1  1475.7   156.2 1483.15     166 1487.04   175.7 1490.52
   185.5 1495.85   195.3 1503.64     205 1509.28   224.6 1514.73   244.1 1520.65
   253.8 1523.71   283.1 1532.72   322.2 1544.37   331.9  1545.4   341.7 1547.95
#Mann= 3 , 0 , 0
       0      .1       0   125.1    .045       0   140.1      .1       0
Bank Sta=125.1,140.1
XS Rating Curve= 0 ,0
Exp/Cntr=0.3,0.1

Type RM Length L Ch R = 1 ,19276.3 ,306.4,310.6,314.8
XS GIS Cut Line= 2
     1854668.532      387266.332     1855110.794      387515.363
#Sta/Elev= 30
       0 1535.76    19.9 1528.36    29.9 1525.26    49.8 1521.27    89.6 1512.44
    99.5  1510.6   119.4  1509.1   159.2 1505.31     209 1501.27     219 1500.21
   228.9 1498.76   238.8 1493.41   258.8  1475.6   268.7 1468.08   278.7 1463.75
   291.51460.472   298.6 1458.92   306.6 1459.82   328.4 1462.72   338.4 1463.79
   348.3 1464.26   378.2 1464.46   388.1 1464.84   398.1 1467.36     408 1473.61
   427.9 1488.48   437.9 1494.94   447.8 1500.31   457.8 1502.52   507.6 1507.42
#Mann= 3 , 0 , 0
       0      .1       0   291.5    .045       0   306.6      .1       0
Bank Sta=291.5,306.6
XS Rating Curve= 0 ,0
Exp/Cntr=0.3,0.1

Type RM Length L Ch R = 1 ,18965.6 ,385.6,382.3,378.9
XS GIS Cut Line= 2
     1854615.027       387537.45      1854900.87      387778.572
#Sta/Elev= 30
       0 1488.94    19.7 1486.34    29.5 1485.36    39.4 1485.05      59  1484.1
   118.1  1480.1   147.6 1477.62   157.5 1472.21   167.3 1463.88   177.1  1458.7
     187 1455.14   196.8 1451.98   206.7 1449.04   216.5 1446.88   234.71443.448
   236.2 1443.16     246 1443.18   250.11444.305   255.9  1445.9   265.7 1450.65
   275.6 1460.06   285.4 1471.67   295.2 1482.17   305.1 1490.95   314.9 1494.49
   324.8 1496.42   334.6 1497.72   344.4 1500.73   354.3 1505.61     374 1513.03
#Mann= 3 , 0 , 0
       0      .1       0   234.7    .045       0   250.1      .1       0
Bank Sta=234.7,250.1
XS Rating Curve= 0 ,0
Exp/Cntr=0.3,0.1

Type RM Length L Ch R = 1 ,18583.3 ,405.6,406.4,407
XS GIS Cut Line= 2
     1854424.666      387808.752      1854716.92      387991.568
#Sta/Elev= 30
       0 1464.67    19.7 1461.34    49.2 1453.31    59.1 1450.34    68.9 1449.62
    78.8 1450.47    88.6 1450.51   118.2 1445.07     128 1442.47   147.7 1434.46
   157.6 1431.27   162.2 1429.12   167.4  1426.7   177.2 1426.02   177.31426.047
   187.1 1428.73     197 1432.68   206.8 1437.84   216.7  1446.1   226.5 1455.54
   236.4 1462.04   246.2 1466.21   265.9 1472.97   285.6 1480.48   295.5 1483.69
   305.3 1486.39   315.2 1489.74     325 1494.55   334.9 1498.43   344.7 1500.87
#Mann= 3 , 0 , 0
       0      .1       0   162.2    .045       0   177.3      .1       0
Bank Sta=162.2,177.3
XS Rating Curve= 0 ,0
Exp/Cntr=0.3,0.1

Type RM Length L Ch R = 1 ,18177   ,308.4,303.8,299.1
XS GIS Cut Line= 2
     1854156.121      388067.226     1854469.543      388278.004
#Sta/Elev= 30
       0 1467.83    29.8 1458.53    39.8 1455.56    49.7    1453    79.5 1448.62
    89.5 1446.93   109.3 1442.68   119.3 1440.77   129.2 1439.54   139.2 1435.48
     159 1413.42   178.5 1403.97   178.9 1403.78   188.8 1403.68   193.5 1405.57
   198.8  1407.7   208.7 1413.36   218.7 1416.57   238.6 1421.73   248.5 1424.66
   258.4 1427.82   268.4 1431.55   288.2 1442.12   318.1 1458.59     328 1465.02
     338 1472.04   347.9 1475.23   357.8 1476.78   367.8 1478.67   377.7 1481.44
#Mann= 3 , 0 , 0
       0      .1       0   178.5    .045       0   193.5      .1       0
Bank Sta=178.5,193.5
XS Rating Curve= 0 ,0
Exp/Cntr=0.3,0.1

Type RM Length L Ch R = 1 ,17873.2 ,264.6,263.2,261.6
XS GIS Cut Line= 2
     1854020.339      388370.048     1854306.509      388473.459
#Sta/Elev= 30
       0 1448.39     9.8 1445.32    19.6  1442.6    29.4 1441.11    49.1 1438.82
    58.9 1437.09    68.7 1432.06    78.5 1426.43    88.3  1420.1    98.2 1413.12
     108  1404.4   117.8 1394.94     127 1390.87   127.6  1390.6   137.71394.728
   147.2 1398.79     157 1402.58   176.7  1408.2   186.5 1411.07   196.3 1414.06
   206.1 1417.88   215.9 1422.14   225.8 1425.69   235.6 1428.34   245.4 1430.77
   255.2 1433.09   274.8 1437.34   284.6 1439.35   294.5 1441.18   304.3 1441.69
#Mann= 3 , 0 , 0
       0      .1       0     127    .045       0   137.7      .1       0
Bank Sta=127,137.7
XS Rating Curve= 0 ,0
Exp/Cntr=0.3,0.1

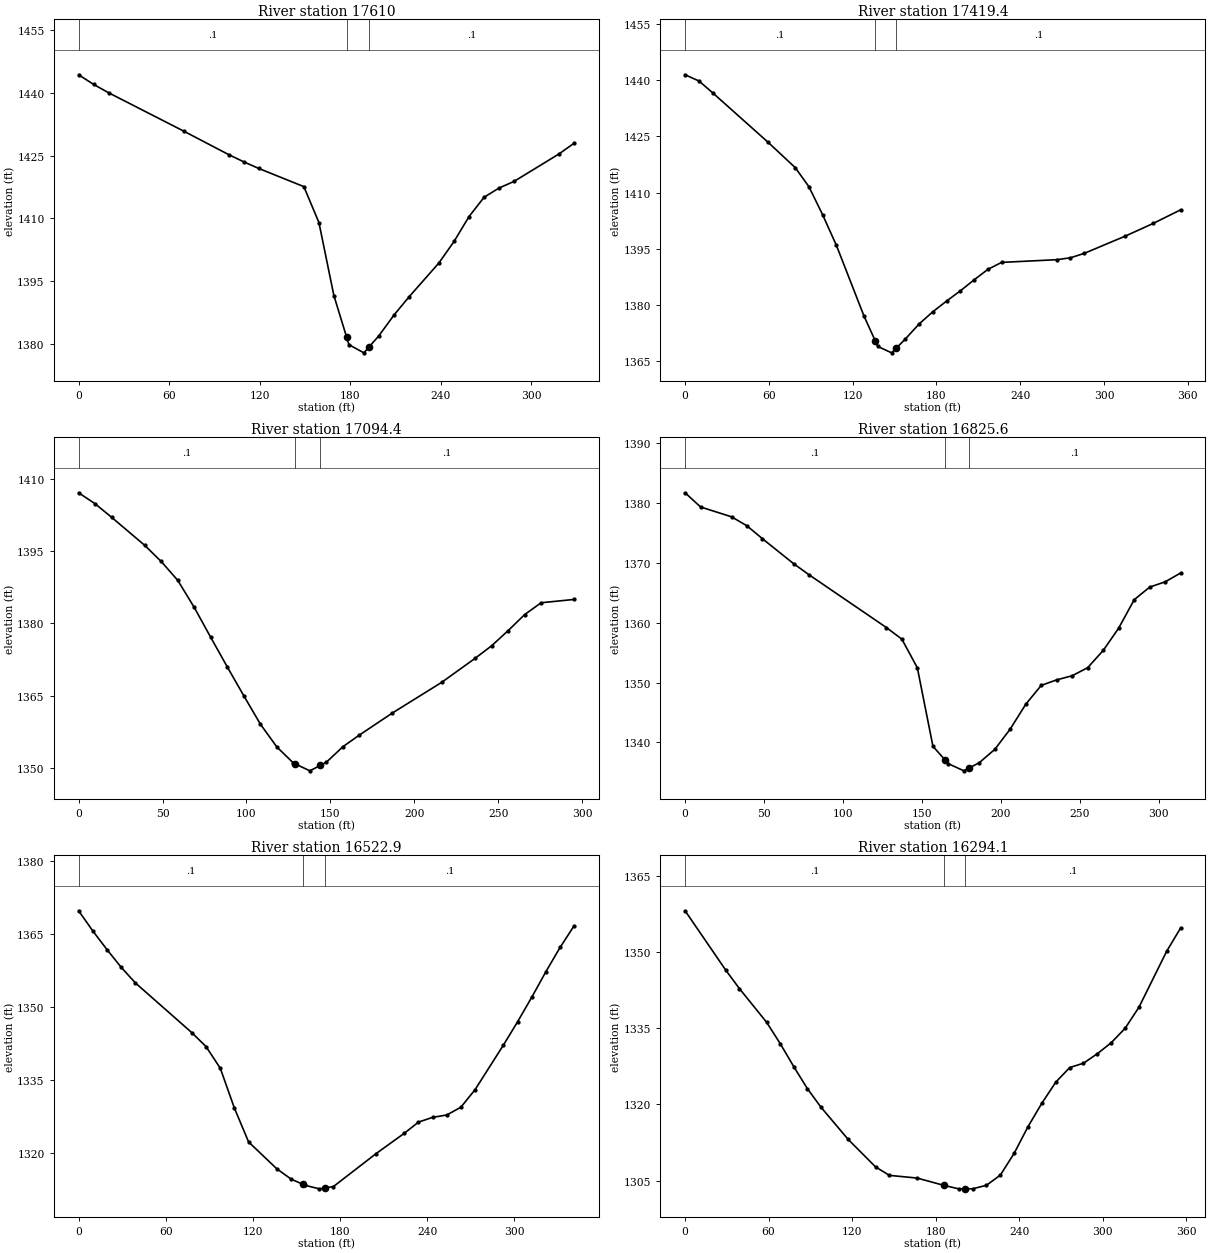
Type RM Length L Ch R = 1 ,17610   ,187.7,190.6,193.3
XS GIS Cut Line= 2
     1853964.594      388619.853     1854278.759      388715.812
#Sta/Elev= 25
       0 1444.37      10 1442.05    19.9 1440.06    69.7 1430.87    99.5 1425.25
   109.5 1423.52   119.4 1421.94   149.3 1417.59   159.3 1408.98   169.2 1391.51
   177.6 1381.62   179.2 1379.74   189.1 1377.79   192.6 1379.23   199.1  1381.9
     209 1386.82     219 1391.18   238.9 1399.34   248.9 1404.48   258.8 1410.42
   268.8 1415.05   278.7 1417.25   288.7 1418.85   318.5 1425.43   328.5 1427.99
#Mann= 3 , 0 , 0
       0      .1       0   177.6    .045       0   192.6      .1       0
Bank Sta=177.6,192.6
XS Rating Curve= 0 ,0
Exp/Cntr=0.3,0.1

Type RM Length L Ch R = 1 ,17419.4 ,337.6,325,312.2
XS GIS Cut Line= 2
     1853931.013      388787.758     1854254.738      388933.117
#Sta/Elev= 27
       0 1441.45     9.9  1439.8    19.7 1436.65    59.1 1423.55    78.9 1416.66
    88.7 1411.57    98.6 1404.01   108.4 1395.89   128.1 1377.08   136.21370.432
     138 1368.95   147.9 1367.24   151.3 1368.52   157.7 1370.92   167.6 1374.95
   177.4  1378.2   187.3 1381.07   197.2 1383.81     207 1386.72   216.9 1389.53
   226.7 1391.38   266.2  1392.1     276 1392.61   285.9 1393.79   315.4 1398.42
   335.2 1401.77   354.9 1405.41
#Mann= 3 , 0 , 0
       0      .1       0   136.2    .045       0   151.3      .1       0
Bank Sta=136.2,151.3
XS Rating Curve= 0 ,0
Exp/Cntr=0.3,0.1

Type RM Length L Ch R = 1 ,17094.4 ,265.7,268.9,272
XS GIS Cut Line= 2
     1853966.144      389170.641     1854258.782      389131.269
#Sta/Elev= 27
       0 1407.16     9.8 1404.88    19.7 1402.05    39.4 1396.23    49.2 1392.88
      59 1388.99    68.9 1383.33    78.7 1377.12    88.6 1370.95    98.4 1364.98
   108.3 1359.07   118.1 1354.33     128 1350.98   128.9 1350.83   137.8 1349.36
   143.9 1350.47   147.6 1351.14   157.5 1354.38   167.3  1356.8     187 1361.39
   216.5 1367.79   236.2 1372.73   246.1 1375.35   255.9 1378.49   265.8 1381.84
   275.6  1384.3   295.3 1384.99
#Mann= 3 , 0 , 0
       0      .1       0   128.9    .045       0   143.9      .1       0
Bank Sta=128.9,143.9
XS Rating Curve= 0 ,0
Exp/Cntr=0.3,0.1

Type RM Length L Ch R = 1 ,16825.6 ,300.1,302.7,305.3
XS GIS Cut Line= 2
     1853950.761      389417.561     1854264.662      389419.385
#Sta/Elev= 29
       0 1381.68     9.8 1379.31    29.4 1377.67    39.2 1376.16      49 1374.01
    68.7 1369.85    78.5 1367.99   127.5 1359.18   137.3 1357.24   147.1 1352.47
     157 1339.34   164.8 1337.03   166.8 1336.44   176.6 1335.25   179.8  1335.7
   186.4 1336.62   196.2 1338.84     206 1342.25   215.8 1346.37   225.6 1349.52
   235.4 1350.44   245.2 1351.13     255 1352.47   264.9 1355.37   274.7  1359.1
   284.5 1363.83   294.3 1365.93   304.1 1366.81   313.9 1368.29
#Mann= 3 , 0 , 0
       0      .1       0   164.8    .045       0   179.8      .1       0
Bank Sta=164.8,179.8
XS Rating Curve= 0 ,0
Exp/Cntr=0.3,0.1

Type RM Length L Ch R = 1 ,16522.9 ,232.4,228.8,225.2
XS GIS Cut Line= 2
     1853932.713      389699.278      1854271.23      389741.205
#Sta/Elev= 30
       0 1369.69     9.8 1365.53    19.5 1361.73    29.2 1358.12      39  1354.9
      78 1344.65    87.7 1341.81    97.5 1337.37   107.2  1329.2     117 1322.23
   136.4 1316.73   146.2 1314.62   154.2 1313.56   155.9 1313.33   165.7 1312.61
   169.31312.785   175.4 1313.08   204.7 1319.83   224.2 1324.02   233.9  1326.3
   243.6 1327.28   253.4 1327.77   263.1 1329.36   272.9 1332.98   292.4 1342.12
   302.1 1346.88   311.9 1351.94   321.6 1357.17   331.4 1362.17   341.1 1366.62
#Mann= 3 , 0 , 0
       0      .1       0   154.2    .045       0   169.3      .1       0
Bank Sta=154.2,169.3
XS Rating Curve= 0 ,0
Exp/Cntr=0.3,0.1

Type RM Length L Ch R = 1 ,16294.1 ,109.2,109.2,109.2
XS GIS Cut Line= 3
     1853906.548      389927.412     1854031.366      389950.295
     1854260.264      389941.817
#Sta/Elev= 30
       0  1358.1    29.3 1346.38      39  1342.8    58.6 1336.15    68.3 1331.98
    78.1 1327.42    87.8 1323.12    97.6 1319.46   117.1 1313.13   136.9 1307.69
   146.8 1306.04   166.7 1305.51   186.1 1304.06   196.6 1303.39   201.1 1303.39
   206.6  1303.4   216.5 1304.09   226.5  1306.1   236.4 1310.38   246.4 1315.65
   256.4 1320.28   266.3 1324.38   276.3 1327.25   286.2 1328.11   296.2 1329.98
   306.2 1332.16   316.1 1334.97   326.1 1339.15     346 1350.15     356 1354.72
#Mann= 3 , 0 , 0
       0      .1       0   186.1    .045       0   201.1      .1       0
Bank Sta=186.1,201.1
XS Rating Curve= 0 ,0
Exp/Cntr=0.3,0.1

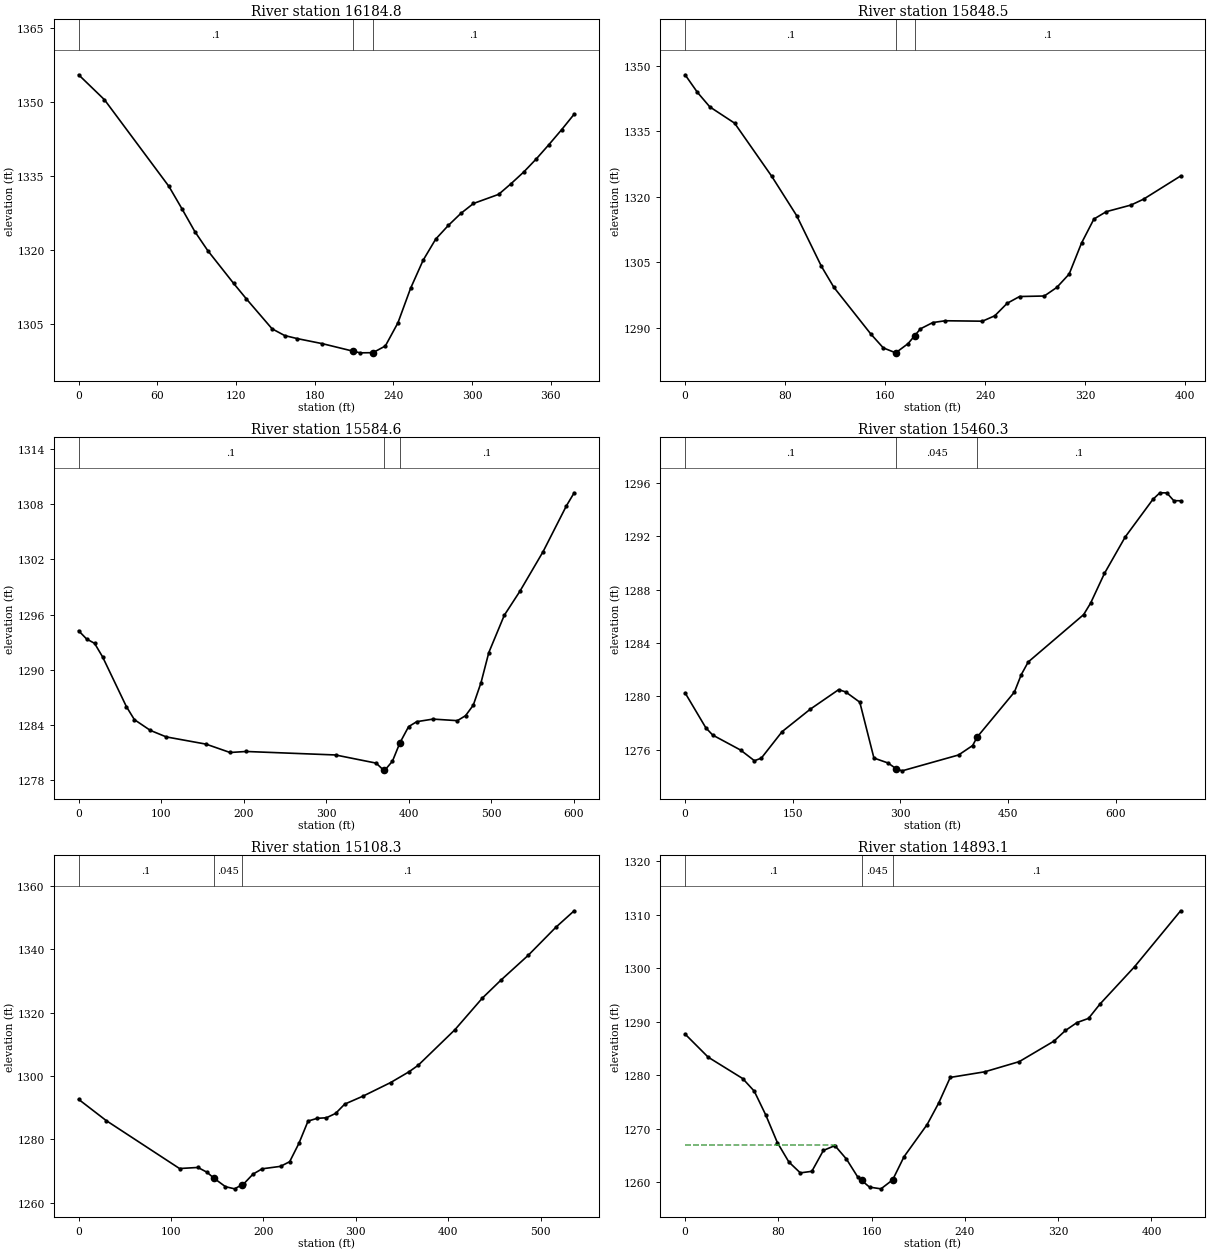
Type RM Length L Ch R = 1 ,16184.8 ,333.5,336.4,339.3
XS GIS Cut Line= 3
     1853890.537      390034.871     1854026.136      390059.731
     1854265.988      390050.848
#Sta/Elev= 30
       0 1355.48    19.7 1350.42    68.9 1332.82    78.8 1328.29    88.6 1323.68
    98.5  1319.8   118.2 1313.16     128 1309.99   147.5 1303.95   157.1 1302.58
   166.7 1301.96   185.9 1300.93   209.4  1299.4   214.7 1299.07   224.4  1299.1
   233.9 1300.46   243.5 1305.16   253.1 1312.13   262.7 1317.85   272.3 1322.14
   281.9 1324.91   291.5 1327.36   301.1 1329.37   320.3 1331.22   329.9 1333.42
   339.5 1335.77   349.1 1338.44   358.7 1341.33   368.3 1344.33   377.9 1347.49
#Mann= 3 , 0 , 0
       0      .1       0   209.4    .045       0   224.4      .1       0
Bank Sta=209.4,224.4
XS Rating Curve= 0 ,0
Exp/Cntr=0.3,0.1

Type RM Length L Ch R = 1 ,15848.5 ,282,263.9,248
XS GIS Cut Line= 2
     1853889.799       390369.11     1854284.755      390403.939
#Sta/Elev= 30
       0 1347.98     9.9 1343.94    19.8 1340.62    39.6  1336.9    69.4 1324.69
    89.2 1315.74     109 1304.14     119 1299.31   148.7 1288.56   158.6 1285.41
   168.41284.292   168.5 1284.28   178.4 1286.39   183.61288.174   188.3 1289.78
   198.2 1291.22   208.2 1291.63   237.9 1291.53   247.8 1292.77   257.7 1295.63
   267.6 1297.18   287.4  1297.3   297.4 1299.26   307.3 1302.33   317.2 1309.43
   327.1 1314.93     337 1316.62   356.8 1318.14   366.8 1319.48   396.5  1324.8
#Mann= 3 , 0 , 0
       0      .1       0   168.4    .045       0   183.6      .1       0
Bank Sta=168.4,183.6
XS Rating Curve= 0 ,0
Exp/Cntr=0.3,0.1

Type RM Length L Ch R = 1 ,15584.6 ,177.4,124.3,78.5
XS GIS Cut Line= 4
     1853715.226      390665.144     1853881.983      390741.683
     1854132.397      390604.617     1854239.204       390527.54
#Sta/Elev= 30
       0 1294.23     9.7 1293.33    19.3 1292.86      29 1291.39    57.9 1285.96
    67.6 1284.54    86.9 1283.37   106.2 1282.66   154.5 1281.87   183.5 1280.96
   203.2 1281.07   311.4 1280.69   360.7  1279.8   369.8 1279.02   370.5 1278.96
   380.4 1280.01   389.41282.003     400 1283.78   409.9 1284.32   429.6  1284.6
   459.1 1284.43     469 1284.97   478.4 1286.12   487.8 1288.58   497.2 1291.85
     516 1295.92   534.8 1298.52     563 1302.85   591.3 1307.85   600.7 1309.27
#Mann= 3 , 0 , 0
       0      .1       0   369.8    .045       0   389.4      .1       0
Bank Sta=369.8,389.4
XS Rating Curve= 0 ,0
Exp/Cntr=0.3,0.1

Type RM Length L Ch R = 1 ,15460.3 ,250.5,352,443.2
XS GIS Cut Line= 5
     1853677.699      390747.126     1853805.629      390790.954
     1853982.646      390784.098     1854047.611      390710.323
     1854326.191      390681.695
#Sta/Elev= 30
       0 1280.26      29 1277.63    38.6 1277.09    77.3 1275.97    96.6 1275.17
   106.2 1275.36   135.2 1277.35   174.6 1279.04     214  1280.5   223.8 1280.33
   243.5 1279.56   263.2 1275.37   282.8    1275   294.41274.559   302.5 1274.41
   381.2  1275.6   400.8 1276.31   407.11276.946     459 1280.32   468.6 1281.63
   478.3 1282.58   555.5 1286.13   565.2 1286.99   584.5 1289.22   613.5 1291.96
   652.1 1294.78   661.8 1295.27   671.4 1295.26   681.1 1294.68   690.7 1294.67
#Mann= 3 , 0 , 0
       0      .1       0   294.4    .045       0   407.1      .1       0
#XS Ineff= 2 , 0
          223.51 1280.16
Permanent Ineff=
       F       F
Bank Sta=294.4,407.1
XS Rating Curve= 0 ,0
Exp/Cntr=0.3,0.1

Type RM Length L Ch R = 1 ,15108.3 ,232.1,215.2,199.5
XS GIS Cut Line= 2
     1853646.631      390693.266     1853741.476      391221.148
#Sta/Elev= 30
       0 1292.65    29.8 1285.96   109.2 1270.81   129.1 1271.15     139 1269.63
   146.11267.834   158.9 1265.08   168.8  1264.4     177 1265.72   178.8 1266.01
   188.7 1269.04   198.6 1270.72   218.5  1271.5   228.4 1272.97   238.4 1278.76
   248.3  1285.8   258.2 1286.66   268.2 1286.84   278.1 1288.21     288 1291.15
   307.9 1293.68   337.7 1297.96   357.6 1301.36   367.5 1303.41   407.2 1314.62
     437 1324.64   456.9 1330.25   486.7 1338.16   516.5 1346.98   536.3 1352.18
#Mann= 3 , 0 , 0
       0      .1       0   146.1    .045       0     177      .1       0
Bank Sta=146.1,177
XS Rating Curve= 0 ,0
Exp/Cntr=0.3,0.1

Type RM Length L Ch R = 1 ,14893.1 ,465.5,480,492
XS GIS Cut Line= 2
      1853361.68      390825.432     1853690.976       391094.17
#Sta/Elev= 30
       0 1287.68    19.8 1283.37    49.4 1279.38    59.3 1277.03    69.2 1272.57
    79.1 1267.44      89  1263.8    98.8 1261.77   108.7 1262.06   118.6 1265.96
   128.5 1266.86   138.4 1264.34   148.3 1260.92   151.41260.353   158.2 1259.11
     168 1258.79     1781260.464   187.8  1264.8   207.6  1270.8   217.5 1274.81
   227.4 1279.59     257 1280.64   286.6 1282.54   316.3 1286.36   326.2 1288.35
   336.1 1289.83     346 1290.61   355.8 1293.28   385.5 1300.26     425  1310.7
#Mann= 3 , 0 , 0
       0      .1       0   151.4    .045       0     178      .1       0
#XS Ineff= 2 , 0
          128.34 1266.94
Permanent Ineff=
       F       F
Bank Sta=151.4,178
XS Rating Curve= 0 ,0
Exp/Cntr=0.3,0.1

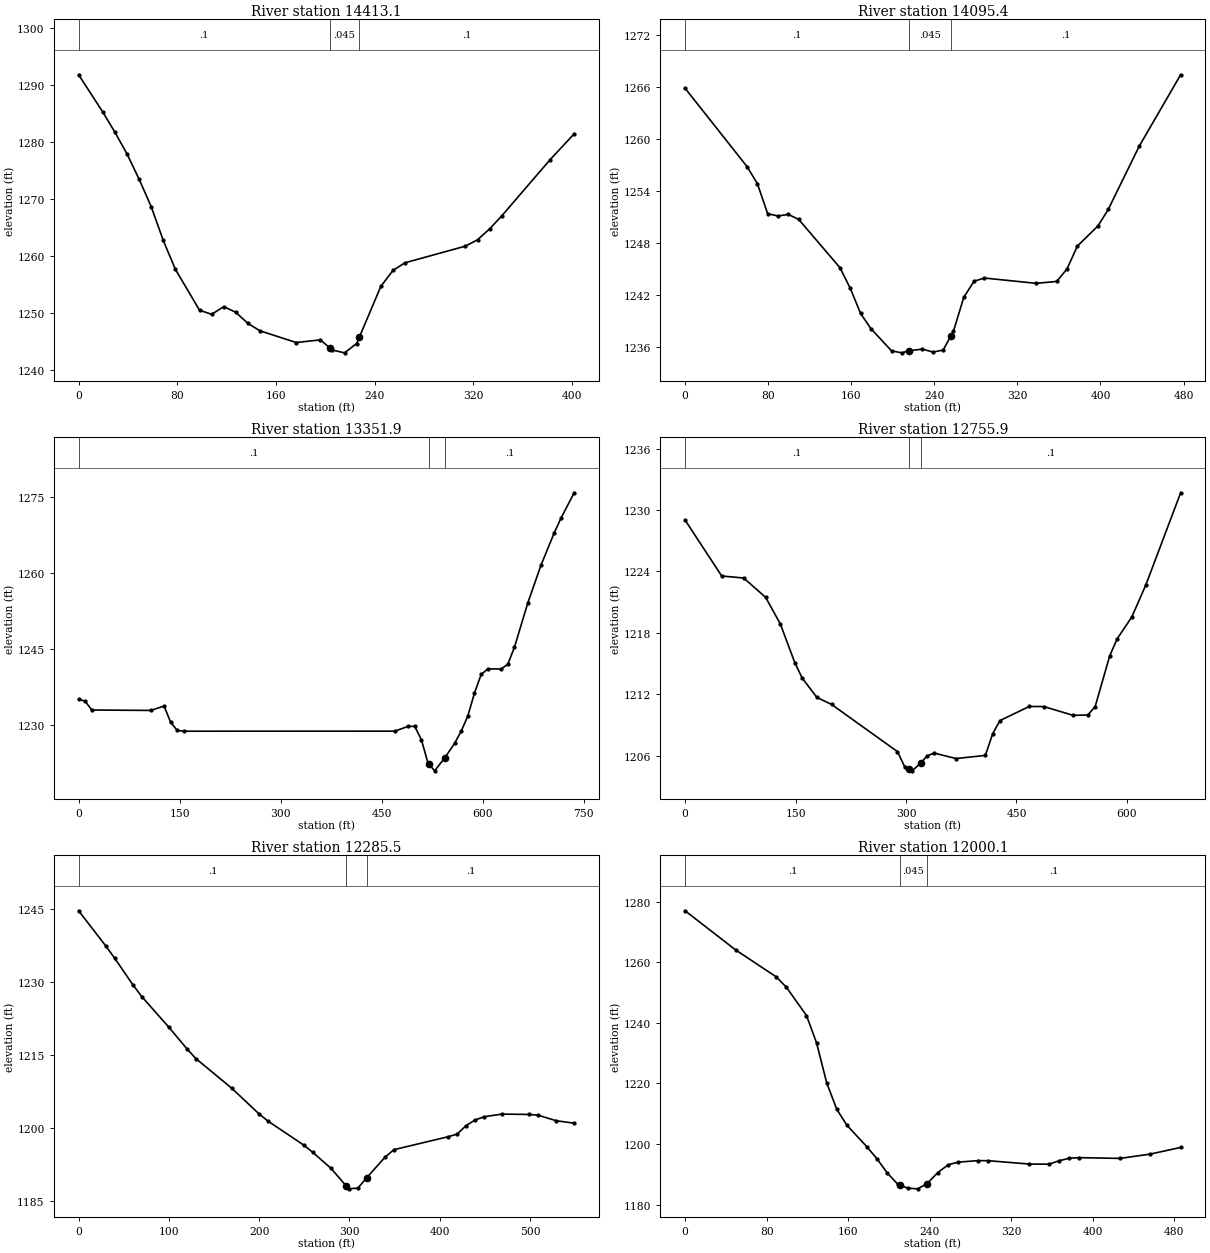
Type RM Length L Ch R = 1 ,14413.1 ,330.7,317.6,304.3
XS GIS Cut Line= 2
     1853080.273      390925.183     1853194.997      391310.071
#Sta/Elev= 30
       0 1291.72    19.6 1285.18    29.4 1281.65    39.2 1277.84      49 1273.41
    58.8 1268.59    68.6 1262.65    78.4  1257.6      98 1250.41   107.8  1249.7
   117.6 1251.04   127.3 1250.06   137.1 1248.12   146.9 1246.81   176.3 1244.75
   195.9 1245.21   203.41243.848   205.7 1243.43   215.5 1242.94   225.3 1244.57
   227.41245.631   244.9 1254.59   254.7 1257.39   264.5 1258.74   313.5 1261.66
   323.3 1262.78     333 1264.67   342.8 1266.94     382  1276.8   401.6 1281.36
#Mann= 3 , 0 , 0
       0      .1       0   203.4    .045       0   227.4      .1       0
Bank Sta=203.4,227.4
XS Rating Curve= 0 ,0
Exp/Cntr=0.3,0.1

Type RM Length L Ch R = 1 ,14095.4 ,734.5,743.5,752.4
XS GIS Cut Line= 2
     1852706.669       391096.56     1853047.523      391430.458
#Sta/Elev= 30
       0 1265.84    59.6  1256.8    69.6 1254.83    79.5 1251.35    89.5 1251.09
    99.4 1251.27   109.4 1250.69   149.1 1245.12     159 1242.75     169 1239.83
   178.9 1238.08   198.8 1235.51   208.8 1235.28   215.3 1235.52   228.6 1235.71
   238.6 1235.37   248.5  1235.6     2561237.244   258.4 1237.77   268.4  1241.7
   278.3 1243.56   288.3 1243.92     338 1243.31   357.9 1243.53   367.8 1244.98
   377.7  1247.6   397.6 1249.94   407.6 1251.87   437.4 1259.17   477.2  1267.4
#Mann= 3 , 0 , 0
       0      .1       0   215.3    .045       0     256      .1       0
Bank Sta=215.3,256
XS Rating Curve= 0 ,0
Exp/Cntr=0.3,0.1

Type RM Length L Ch R = 1 ,13351.9 ,603.7,595.9,587.8
XS GIS Cut Line= 3
     1852234.327      391459.421      1852492.03      391752.767
     1852634.033      392067.577
#Sta/Elev= 30
       0 1235.11     9.8 1234.68    19.5 1232.96   107.4 1232.88   126.9 1233.75
   136.7 1230.52   146.4 1228.94   156.2 1228.78   469.4 1228.79   489.1 1229.73
     499 1229.75   508.9 1227.11   518.7 1222.51   520.41222.245   528.6 1220.96
   543.4 1223.47   558.2 1226.36   568.1  1228.8   577.9 1231.79   587.8 1236.31
   597.7 1239.97   607.6 1241.08   627.3 1241.05   637.2 1241.97     647  1245.3
   666.8 1254.02   686.5 1261.52   706.2 1267.92   716.1 1270.78   735.8 1275.82
#Mann= 3 , 0 , 0
       0      .1       0   520.4    .045       0   543.4      .1       0
Bank Sta=520.4,543.4
XS Rating Curve= 0 ,0
Exp/Cntr=0.3,0.1

Type RM Length L Ch R = 1 ,12755.9 ,482.2,470.5,458.7
XS GIS Cut Line= 3
     1851860.143       391747.04     1852233.957      392224.851
     1852283.868      392268.491
#Sta/Elev= 30
       0 1229.02    49.7 1223.56    79.6 1223.36   109.4 1221.47   129.3 1218.88
   149.2 1215.05   159.1 1213.58     179 1211.69   198.9 1211.01   288.4  1206.4
   298.4 1204.89   303.91204.684   308.3 1204.52   320.81205.334   328.2 1205.96
   338.1 1206.26     368 1205.72   407.8 1206.03   417.7 1208.14   427.6 1209.43
   467.4 1210.81   487.3  1210.8   527.1 1209.94     547 1209.98   556.9  1210.8
   576.8 1215.78   586.8 1217.42   606.7 1219.56   625.6 1222.66     673 1231.69
#Mann= 3 , 0 , 0
       0      .1       0   303.9    .045       0   320.8      .1       0
Bank Sta=303.9,320.8
XS Rating Curve= 0 ,0
Exp/Cntr=0.3,0.1

Type RM Length L Ch R = 1 ,12285.5 ,304.8,285.4,265.7
XS GIS Cut Line= 2
     1851593.888      392270.816     1852109.573      392459.062
#Sta/Elev= 30
       0 1244.64    29.9 1237.46    39.9 1234.91    59.9  1229.5    69.9 1227.03
    99.8 1220.77   119.8 1216.35   129.8 1214.31   169.7  1208.2   199.6 1202.98
   209.6 1201.48   249.5 1196.52   259.5 1195.03   279.5 1191.77   296.41188.161
   299.4 1187.55   309.4  1187.7   319.31189.858   339.4 1194.04   349.3 1195.59
   409.2 1198.24   419.2 1198.78   429.2 1200.53   439.2 1201.68   449.2 1202.35
   469.1  1202.9   499.1 1202.82     509 1202.67     529 1201.54     549 1201.03
#Mann= 3 , 0 , 0
       0      .1       0   296.4    .045       0   319.3      .1       0
Bank Sta=296.4,319.3
XS Rating Curve= 0 ,0
Exp/Cntr=0.3,0.1

Type RM Length L Ch R = 1 ,12000.1 ,428,425.4,422.7
XS GIS Cut Line= 2
     1851630.228      392750.564     1852060.683      392524.619
#Sta/Elev= 30
       0 1276.95    49.6 1264.03    89.3 1255.18    99.2 1251.81   119.1  1242.4
     129 1233.36   138.9 1220.22   148.8 1211.46   158.7 1206.23   178.6 1199.01
   188.5 1195.03   198.4 1190.44   208.4 1186.85   210.41186.565   218.3 1185.44
   228.2 1185.22   237.41186.948     248  1190.6     258 1193.13   267.9 1194.03
   287.7 1194.53   297.6  1194.5   337.3 1193.41   357.2 1193.35   367.1 1194.51
     377 1195.31   386.9 1195.51   426.6 1195.26   456.4 1196.68   486.2 1198.88
#Mann= 3 , 0 , 0
       0      .1       0   210.4    .045       0   237.4      .1       0
Bank Sta=210.4,237.4
XS Rating Curve= 0 ,0
Exp/Cntr=0.3,0.1

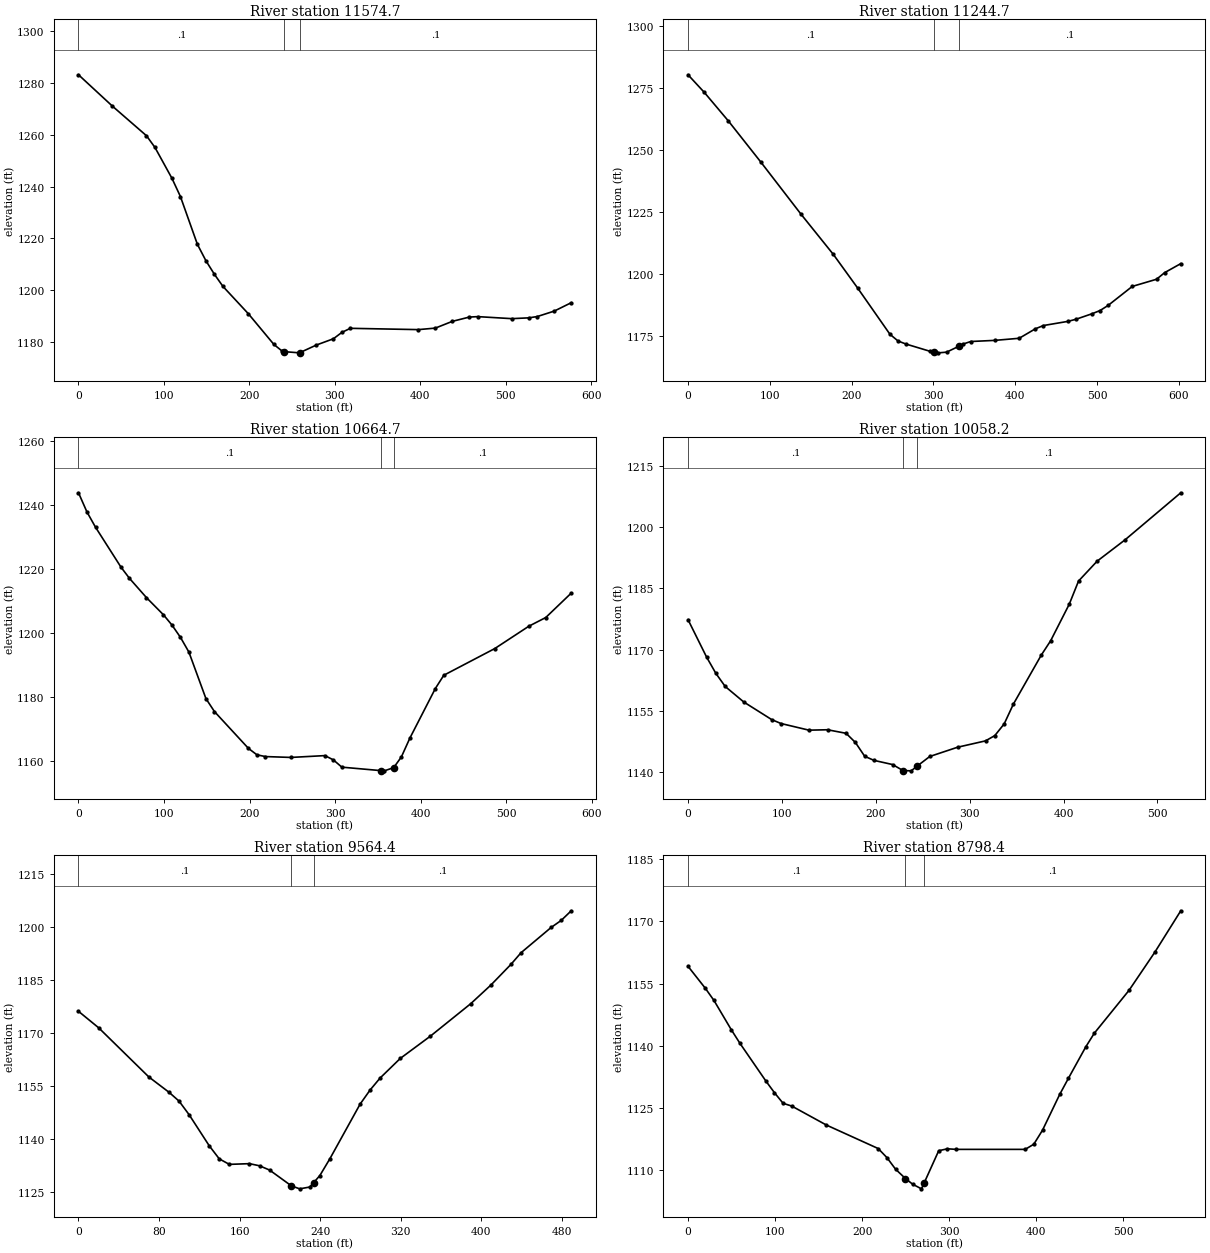
Type RM Length L Ch R = 1 ,11574.7 ,331.9,330,328.1
XS GIS Cut Line= 2
     1851873.544      393131.095     1852349.234      392804.866
#Sta/Elev= 30
       0 1283.02    39.8 1270.92    79.6 1259.55    89.5 1255.05   109.4 1243.16
   119.3 1236.16   139.2 1217.74   149.2 1211.41   159.1 1206.21   169.1 1201.55
   198.9    1191   228.7 1179.22   238.7 1176.56   240.91176.436   258.6 1175.98
   259.2 1176.07   278.5 1178.99   298.4  1181.4   308.3 1183.85   318.2 1185.42
   397.8 1184.92   417.7  1185.5   437.6  1188.1   457.5 1189.75   467.4 1189.92
   507.2 1189.14   527.1 1189.45     537 1189.95   556.9 1192.05   576.8 1195.28
#Mann= 3 , 0 , 0
       0      .1       0   240.9    .045       0   259.2      .1       0
Bank Sta=240.9,259.2
XS Rating Curve= 0 ,0
Exp/Cntr=0.3,0.1

Type RM Length L Ch R = 1 ,11244.7 ,577.7,580,582.4
XS GIS Cut Line= 2
      1852065.43        393422.3       1852530.7      393039.828
#Sta/Elev= 30
       0 1280.29    19.8 1273.24    49.4 1261.67    88.9  1245.2   138.2 1224.14
   177.7 1207.96   207.4 1194.43   246.8 1175.86   256.7 1173.15   266.6  1171.9
   296.2 1168.96     3011168.678   306.1 1168.38     316 1168.65     331 1171.02
   335.7 1171.86   345.6 1172.94   375.2  1173.4   404.8 1174.24   424.6 1178.06
   434.4 1179.37   464.1 1181.03   473.9 1181.86   493.7  1184.1   503.6  1185.4
   513.4 1187.44     543 1195.11   572.7    1198   582.6 1200.66   602.3 1204.29
#Mann= 3 , 0 , 0
       0      .1       0     301    .045       0     331      .1       0
Bank Sta=301,331
XS Rating Curve= 0 ,0
Exp/Cntr=0.3,0.1

Type RM Length L Ch R = 1 ,10664.7 ,604.9,606.5,608
XS GIS Cut Line= 2
     1852359.631      393868.775      1852842.25       393554.13
#Sta/Elev= 30
       0 1243.89     9.9 1237.89    19.9 1233.13    49.7 1220.64    59.6 1217.15
    79.5 1211.12    99.3 1205.77   109.3 1202.55   119.2 1198.72   129.1  1194.1
     149 1179.57   158.9 1175.54   198.7 1164.01   208.6 1162.01   218.5 1161.46
   248.3 1161.19   288.1 1161.76     298 1160.42   307.9 1158.15   353.5 1157.07
   357.6    1157   368.5    1158   377.5 1161.35   387.4 1167.21   417.2 1182.72
   427.1 1186.87   486.7 1195.21   526.5 1202.19   546.3 1204.91   576.1 1212.54
#Mann= 3 , 0 , 0
       0      .1       0   353.5    .045       0   368.5      .1       0
Bank Sta=353.5,368.5
XS Rating Curve= 0 ,0
Exp/Cntr=0.3,0.1

Type RM Length L Ch R = 1 ,10058.2 ,472.9,493.8,514.6
XS GIS Cut Line= 2
     1852655.281       394317.45     1853112.127        394058.9
#Sta/Elev= 30
       0 1177.37    19.8 1168.21    29.7 1164.22    39.6 1161.03    59.4 1157.23
    89.1 1152.93      99 1151.97   128.8 1150.34   148.6 1150.44   168.4 1149.57
   178.3 1147.33   188.2 1143.95   198.1 1142.95   217.9 1141.93     2291140.461
   237.7 1140.39   244.1 1141.55   257.5  1143.9   287.2 1146.17   316.9 1147.72
   326.8 1149.01   336.8 1151.88   346.6 1156.72   376.4 1168.74   386.3 1172.22
   406.1 1181.15     416 1186.82   435.8 1191.68   465.5 1196.89   524.9 1208.41
#Mann= 3 , 0 , 0
       0      .1       0     229    .045       0   244.1      .1       0
Bank Sta=229,244.1
XS Rating Curve= 0 ,0
Exp/Cntr=0.3,0.1

Type RM Length L Ch R = 1 ,9564.4  ,763.6,766,768.4
XS GIS Cut Line= 2
     1852607.198      394578.869     1853058.465      394768.283
#Sta/Elev= 30
       0 1176.14      20 1171.49    69.9 1157.57    89.9 1153.25    99.9 1150.74
   109.9 1146.89   129.8 1138.14   139.8 1134.42   149.8 1132.86   169.8 1133.06
   179.8 1132.46   189.8 1131.25   211.5 1126.77   219.7 1125.94   229.7 1126.45
   233.51127.681   239.7 1129.69   249.7 1134.46   279.7  1149.9   289.6 1153.88
   299.6 1157.29   319.6 1162.82   349.6 1169.14   389.5 1178.28   409.5 1183.54
   429.5 1189.41   439.5  1192.7   469.4 1199.85   479.4 1201.84   489.4 1204.57
#Mann= 3 , 0 , 0
       0      .1       0   211.5    .045       0   233.5      .1       0
Bank Sta=211.5,233.5
XS Rating Curve= 0 ,0
Exp/Cntr=0.3,0.1

Type RM Length L Ch R = 1 ,8798.4  ,611.3,623.6,635.9
XS GIS Cut Line= 2
     1852041.731      394922.526     1852542.064      395186.998
#Sta/Elev= 30
       0 1159.19    19.9 1153.88    29.8 1150.95    49.6 1143.92    59.6 1140.62
    89.4 1131.52    99.3 1128.69   109.2 1126.14   119.1 1125.48   158.9  1120.9
   218.4 1115.23   228.4 1113.05   238.3 1110.26   249.71107.994   258.1 1106.61
   268.1 1105.51     271 1106.84   287.9  1114.7   297.9 1115.17   307.8 1115.03
   387.2 1115.03   397.1 1116.27   407.1 1119.65   426.9  1128.3   436.9 1132.19
   456.7 1139.72   466.6 1143.05   506.4 1153.37   536.2 1162.62   565.9 1172.58
#Mann= 3 , 0 , 0
       0      .1       0   249.7    .045       0     271      .1       0
Bank Sta=249.7,271
XS Rating Curve= 0 ,0
Exp/Cntr=0.3,0.1