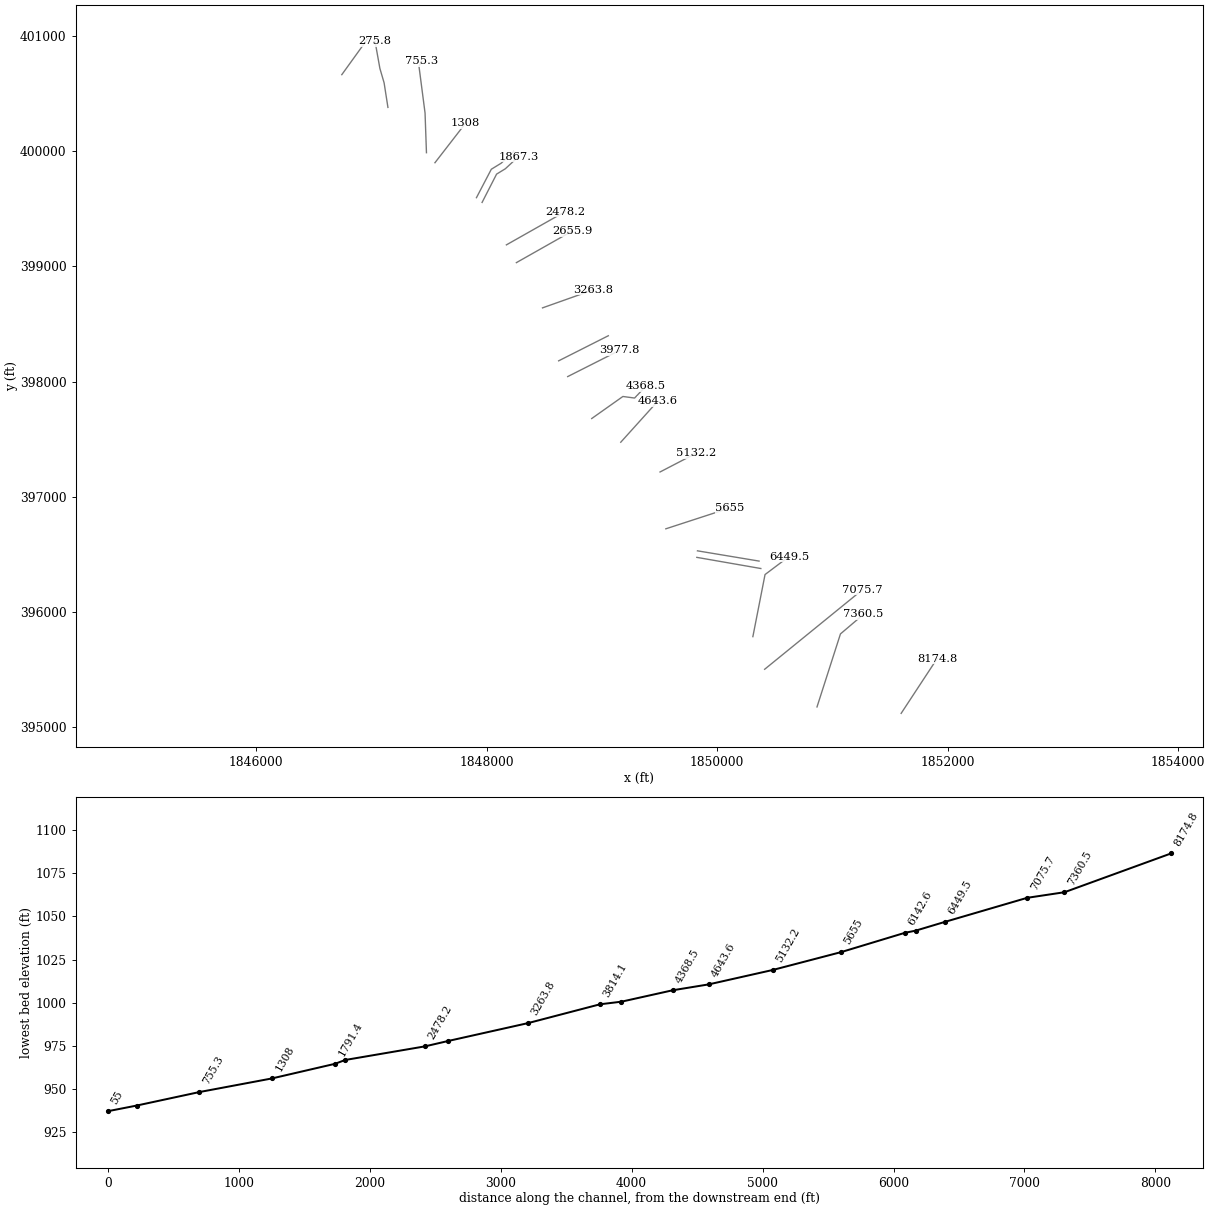
HEC-RAS study AaronCk.prj: AaronCk

--- AaronCk.g01 (geometry) --- (continued)

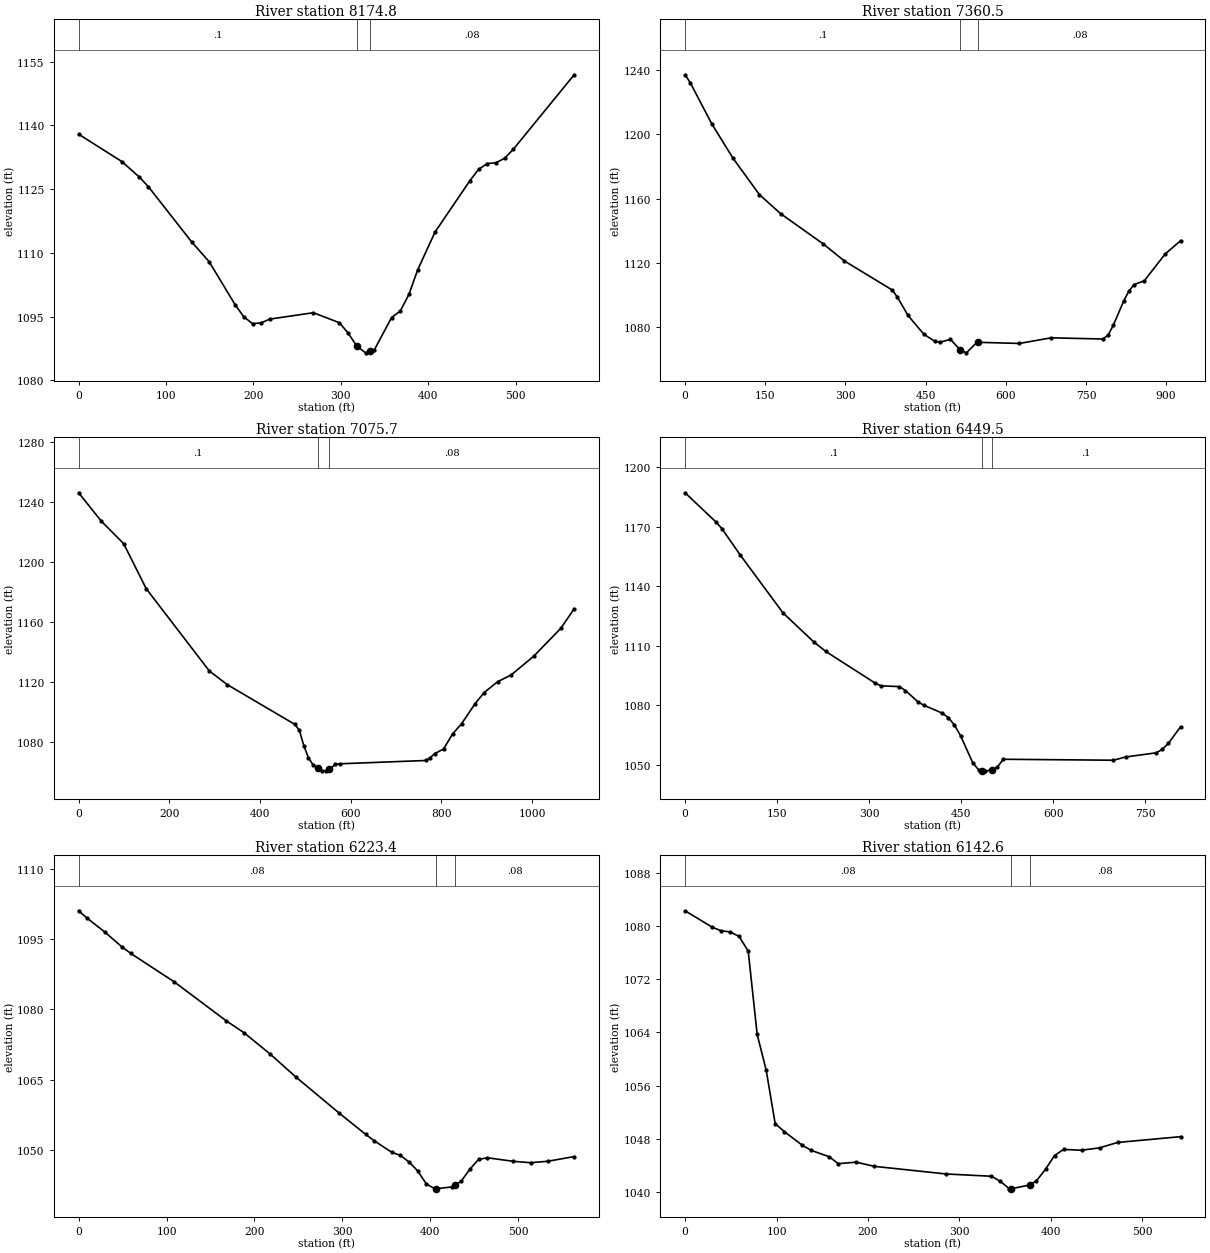
Type RM Length L Ch R = 1 ,8174.8  ,807.7,814.3,820.9
XS GIS Cut Line= 2
     1851596.874      395122.268     1851908.002      395596.038
#Sta/Elev= 30
       0 1137.95    49.7 1131.47    69.6 1127.82    79.6 1125.63   129.3 1112.58
   149.2 1107.95     179 1097.79   188.9 1094.95   198.9 1093.33   208.8 1093.52
   218.8 1094.41   268.5 1095.91   298.3 1093.55   308.3  1091.1   318.11088.061
   328.2 1086.46   333.51086.813   338.1 1087.12     358 1094.78   367.9 1096.31
   377.9 1100.27   387.8 1106.01   407.7 1114.92   447.5 1126.99   457.4 1129.66
   467.4 1131.04   477.3 1131.22   487.2 1132.26   497.2  1134.4   566.8 1151.94
#Mann= 3 , 0 , 0
       0      .1       0   318.1    .045       0   333.5     .08       0
Bank Sta=318.1,333.5
XS Rating Curve= 0 ,0
Exp/Cntr=0.3,0.1

Type RM Length L Ch R = 1 ,7360.5  ,298,284.8,271.5
XS GIS Cut Line= 3
     1850866.873      395178.203     1851070.348      395811.643
        1851270.      395980.913
#Sta/Elev= 30
       0 1237.11     9.9 1232.01    49.6 1206.73    89.4 1185.25     139 1162.51
   178.7 1150.64   258.2 1131.86   297.9 1121.22   387.3 1103.14   397.2 1098.66
   417.1 1087.23   446.8 1075.51   466.7 1071.28   476.6 1070.59   496.5 1072.36
   514.51065.821   526.3 1063.98   546.2 1070.59   548.81070.524   625.6 1069.83
   684.7 1073.33   781.6  1072.6   791.4 1074.99     801 1081.06   820.4 1096.12
   830.1 1102.34   839.8 1106.45   859.2 1108.89     898 1125.48   927.1 1133.83
#Mann= 3 , 0 , 0
       0      .1       0   514.5    .045       0   548.8     .08       0
Bank Sta=514.5,548.8
XS Rating Curve= 0 ,0
Exp/Cntr=0.3,0.1

Type RM Length L Ch R = 1 ,7075.7  ,610.2,626.1,642.1
XS GIS Cut Line= 2
     1850412.751      395504.903     1851260.557      396194.316
#Sta/Elev= 30
       0 1246.42    49.7 1227.58    99.3 1212.45     149  1182.4   288.1 1127.46
   327.8 1118.29   476.8 1091.76   486.8 1087.72   496.7 1077.41   506.6 1069.53
   516.6 1064.91   526.81062.499   536.4 1060.87   546.4 1060.74     553 1061.74
   566.2 1065.03   576.2 1065.44   764.9 1067.65   774.8 1069.34   784.8 1072.21
   804.6 1075.27   824.5 1085.36   844.4 1092.17   874.2 1105.57     894 1112.97
   923.9 1120.25   953.7 1124.77  1003.3 1137.22  1062.9  1155.8  1092.7 1168.96
#Mann= 3 , 0 , 0
       0      .1       0   526.8    .045       0     553     .08       0
Bank Sta=526.8,553
XS Rating Curve= 0 ,0
Exp/Cntr=0.3,0.1

Type RM Length L Ch R = 1 ,6449.5  ,265.7,226.1,185.5
XS GIS Cut Line= 3
     1850310.525      395787.997     1850416.091      396326.626
     1850623.242      396482.299
#Sta/Elev= 30
       0 1187.18    49.9 1172.56    59.9 1169.13    89.8 1155.83   159.7 1126.54
   209.6 1111.97   229.5 1107.08   309.4 1091.22   319.4 1089.74   349.3 1089.37
   359.3 1087.37   379.2 1081.81   389.2 1079.95   419.1 1076.02   429.1 1073.74
   439.1 1070.02   449.1 1064.61     469 1050.94     479  1047.2   484.91046.994
     489 1046.85   500.11047.158     509 1048.72   518.9 1052.69   698.4 1052.21
   718.3 1053.85   768.1 1055.94   778.1 1057.68   788.1 1060.76     808 1069.12
#Mann= 3 , 0 , 0
       0      .1       0   484.9    .045       0   500.1      .1       0
Bank Sta=484.9,500.1
XS Rating Curve= 0 ,0
Exp/Cntr=0.3,0.1

Type RM Length L Ch R = 1 ,6223.4  ,86.6,80.8,83
XS GIS Cut Line= 2
     1849824.248      396475.689     1850379.639       396378.89
#Sta/Elev= 30
       0 1101.01     9.9  1099.4    29.7 1096.49    49.4 1093.29    59.3 1091.92
   108.8 1085.85   168.1 1077.52   187.9 1075.04   217.6 1070.51   247.3 1065.54
   296.7 1057.82   326.4 1053.35   336.3 1051.97   356.1 1049.52     366 1048.85
   375.8 1047.46   385.7 1045.55   395.6 1042.76   405.5 1041.71   406.41041.727
   425.3 1042.13   428.11042.467   435.2 1043.32   445.1  1045.9     455 1047.97
   464.9 1048.34   494.5 1047.58   514.3 1047.28   534.1  1047.6   563.8 1048.59
#Mann= 3 , 0 , 0
       0     .08       0   406.4    .045       0   428.1     .08       0
Bank Sta=406.4,428.1
XS Rating Curve= 0 ,0
Exp/Cntr=0.3,0.1

Type RM Length L Ch R = 1 ,6142.6  ,467.2,487.6,502.2
XS GIS Cut Line= 2
      1849829.94      396532.333     1850364.417      396443.357
#Sta/Elev= 30
       0 1082.27    29.6 1079.81    39.4 1079.26    49.3  1079.1    59.1 1078.41
      69 1076.21    78.8 1063.69    88.7  1058.3    98.5 1050.28   108.4  1049.1
   128.1 1047.04   137.9 1046.27   157.6 1045.31   167.5 1044.27   187.2  1044.5
   206.9 1043.87   285.7 1042.72     335 1042.38   344.8 1041.61   354.6 1040.49
   356.71040.508   376.71041.063   384.2  1041.7   394.1 1043.44   403.9 1045.49
   413.8 1046.41   433.5 1046.29   453.2 1046.65   472.9 1047.46   541.8 1048.33
#Mann= 3 , 0 , 0
       0     .08       0   356.7    .045       0   376.7     .08       0
Bank Sta=356.7,376.7
XS Rating Curve= 0 ,0
Exp/Cntr=0.3,0.1

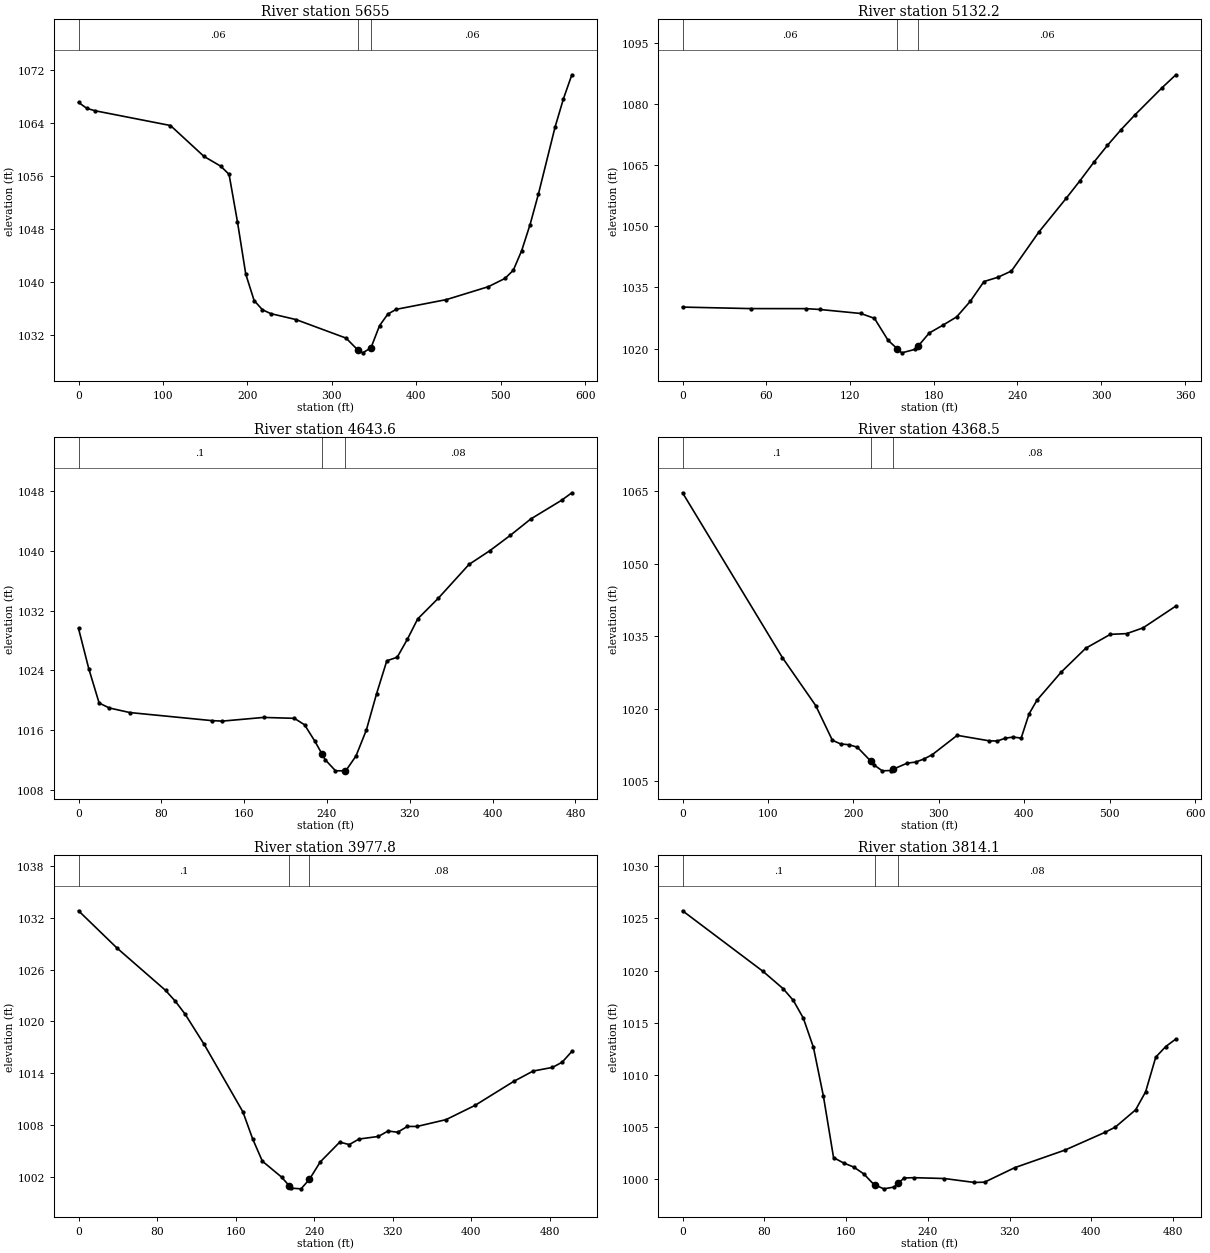
Type RM Length L Ch R = 1 ,5655    ,518.2,522.8,526.2
XS GIS Cut Line= 2
     1849555.566      396723.416     1850111.144      396904.415
#Sta/Elev= 30
       0 1067.06     9.9 1066.16    19.8  1065.8   108.9 1063.58   148.6 1058.92
   168.4 1057.45   178.3 1056.22   188.2 1049.09   198.1 1041.16     208 1037.18
   217.9 1035.79   227.8 1035.21   257.5 1034.32   316.9 1031.52   330.51029.767
   336.7  1029.3   346.41030.063   356.5 1033.39   366.4 1035.15   376.3 1035.86
   435.8 1037.33   485.3 1039.27   505.1 1040.52     515 1041.76   524.9 1044.72
   534.8 1048.63   544.7 1053.24   564.5 1063.38   574.4 1067.63   584.3 1071.23
#Mann= 3 , 0 , 0
       0     .06       0   330.5    .045       0   346.4     .06       0
Bank Sta=330.5,346.4
XS Rating Curve= 0 ,0
Exp/Cntr=0.3,0.1

Type RM Length L Ch R = 1 ,5132.2  ,480.5,488.6,496.6
XS GIS Cut Line= 2
     1849505.197      397216.395     1849818.962      397379.267
#Sta/Elev= 27
       0 1030.18    49.1 1029.81    88.4  1029.8    98.2  1029.6   127.7 1028.61
   137.5 1027.42   147.3 1022.01   153.9 1019.94   157.1 1018.94   166.9 1019.82
   168.9 1020.63   176.8 1023.82   186.6 1025.74   196.4 1027.77   206.2 1031.61
     216 1036.46   225.9  1037.5   235.7 1039.05   255.3 1048.61     275 1056.95
   284.8 1061.24   294.6 1065.71   304.4 1069.89   314.2 1073.76   324.1 1077.38
   343.7 1084.11   353.5 1087.26
#Mann= 3 , 0 , 0
       0     .06       0   153.9    .045       0   168.9     .06       0
Bank Sta=153.9,168.9
XS Rating Curve= 0 ,0
Exp/Cntr=0.3,0.1

Type RM Length L Ch R = 1 ,4643.6  ,280.3,275.1,269.9
XS GIS Cut Line= 2
     1849164.465      397474.525     1849483.654       397828.35
#Sta/Elev= 30
       0 1029.61     9.9 1024.24    19.9 1019.65    29.8 1018.99    49.6 1018.38
   129.1  1017.3     139 1017.24   178.7 1017.73   208.5 1017.61   218.4 1016.74
   228.3 1014.55   235.21012.846   238.3 1012.08   248.2 1010.61   257.2  1010.6
   258.1  1010.6     268 1012.58     278 1016.04   287.9  1020.9   297.8  1025.3
   307.8 1025.76   317.7 1028.18   327.6 1030.88   347.5 1033.64   377.2 1038.16
   397.1 1039.97     417 1042.03   436.8 1044.22   466.6 1046.72   476.5 1047.72
#Mann= 3 , 0 , 0
       0      .1       0   235.2    .045       0   257.2     .08       0
Bank Sta=235.2,257.2
XS Rating Curve= 0 ,0
Exp/Cntr=0.3,0.1

Type RM Length L Ch R = 1 ,4368.5  ,393.8,390.7,387.5
XS GIS Cut Line= 4
      1848912.54      397680.065     1849182.976      397871.349
     1849284.469      397857.767     1849383.465      397962.084
#Sta/Elev= 30
       0 1064.68   116.9  1030.6   155.9 1020.68   175.4 1013.51   185.1 1012.75
   194.8 1012.59   204.6 1012.08   220.41009.186   224.1 1008.42   233.8 1007.19
   243.6 1007.26   246.41007.516     263 1008.78   272.8    1009   282.5 1009.63
   292.3 1010.53   321.5 1014.53   359.2 1013.39   368.5 1013.36   377.8 1013.94
   387.1 1014.17   396.4 1013.96   405.7 1018.99     415 1021.82   443.2 1027.59
     472 1032.54   500.8 1035.41   519.9 1035.56   539.1 1036.75   577.5 1041.26
#Mann= 3 , 0 , 0
       0      .1       0   220.4    .045       0   246.4     .08       0
Bank Sta=220.4,246.4
XS Rating Curve= 0 ,0
Exp/Cntr=0.3,0.1

Type RM Length L Ch R = 1 ,3977.8  ,164.1,163.7,163.2
XS GIS Cut Line= 2
     1848704.073      398043.912     1849152.443      398270.458
#Sta/Elev= 30
       0 1032.81    39.4 1028.47    88.6 1023.59    98.5 1022.34   108.4 1020.86
     128 1017.32   167.4 1009.51   177.3 1006.39   187.2  1003.8   206.8 1001.95
   214.6 1000.94   216.7 1000.67   226.6 1000.59   235.11001.684   246.2 1003.71
     266    1006   275.8 1005.72   285.6 1006.36   305.4 1006.66   315.2 1007.29
     325 1007.15   334.9 1007.82   344.8 1007.82   374.3 1008.61   403.8 1010.26
   443.2 1013.04     463 1014.24   482.6 1014.66   492.5 1015.26   502.4 1016.51
#Mann= 3 , 0 , 0
       0      .1       0   214.6    .045       0   235.1     .08       0
Bank Sta=214.6,235.1
XS Rating Curve= 0 ,0
Exp/Cntr=0.3,0.1

Type RM Length L Ch R = 1 ,3814.1  ,553.3,550.3,547.2
XS GIS Cut Line= 2
     1848625.762       398180.59      1849056.67      398398.297
#Sta/Elev= 30
       0 1025.73    78.8 1019.92    98.5 1018.26   108.4 1017.14   118.2 1015.44
   128.1 1012.64   137.9 1007.94   147.8 1002.07   157.6 1001.56   167.5 1001.17
   177.4 1000.51   187.2   999.5   188.6  999.44     197  999.08   206.9  999.25
   210.8999.5927   216.8 1000.12   226.6 1000.15   256.2 1000.07   285.7  999.69
   295.6  999.72   325.1 1001.11   374.4  1002.8   413.8 1004.51   423.7 1005.01
   443.4 1006.65   453.2 1008.38   463.1  1011.7   472.9 1012.72   482.8 1013.44
#Mann= 3 , 0 , 0
       0      .1       0   188.6    .045       0   210.8     .08       0
Bank Sta=188.6,210.8
XS Rating Curve= 0 ,0
Exp/Cntr=0.3,0.1

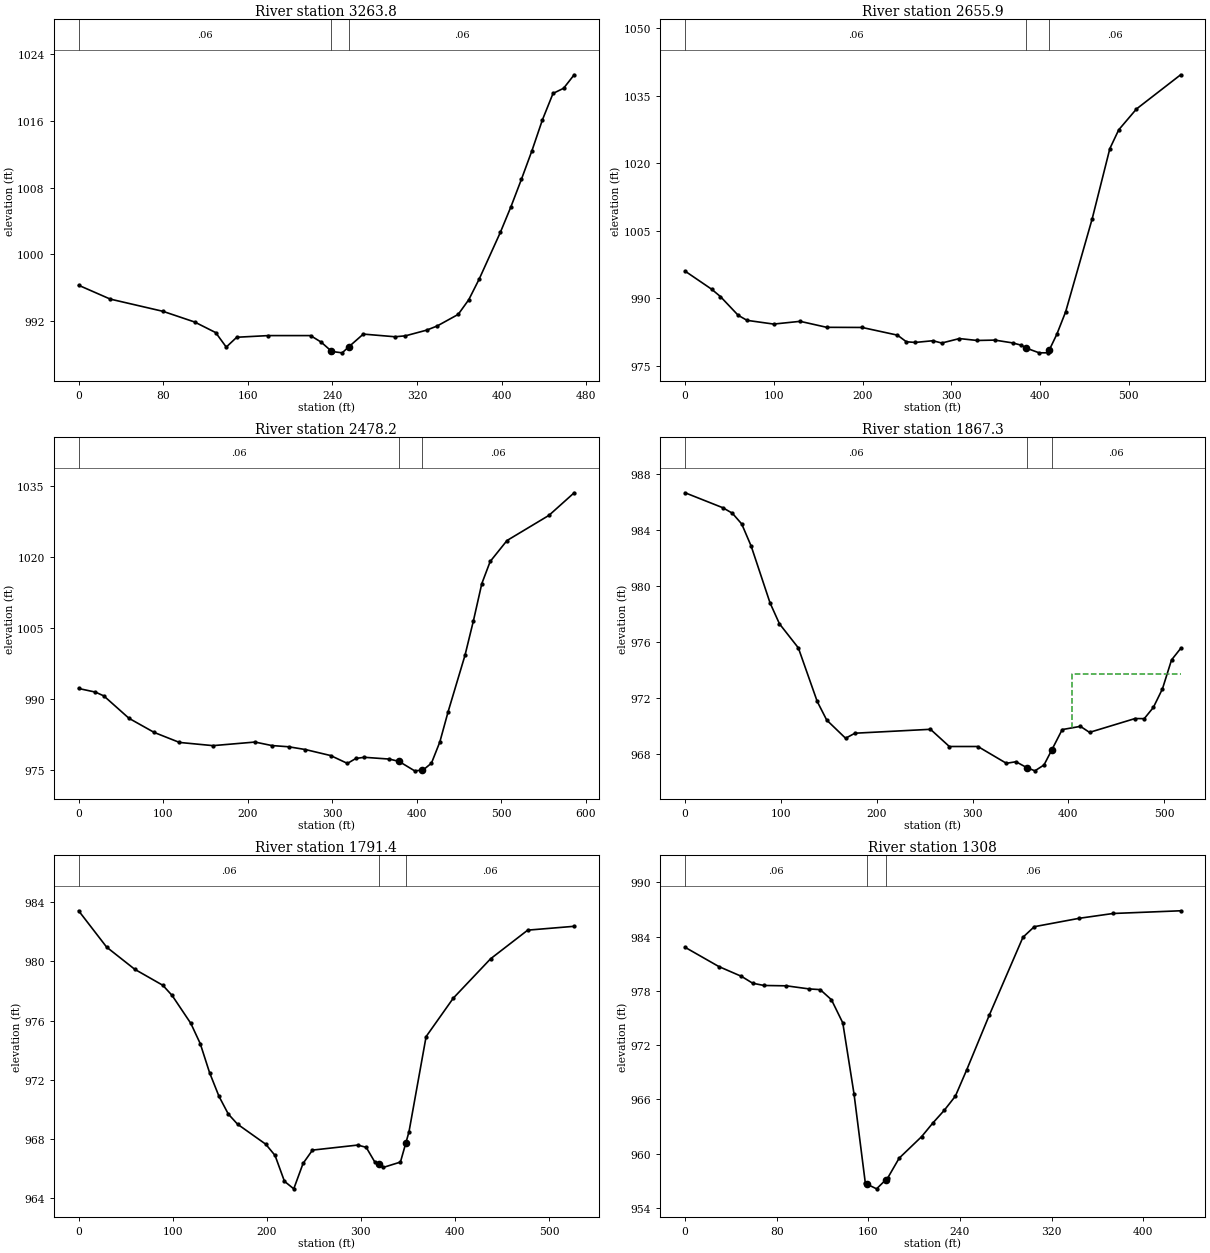
Type RM Length L Ch R = 1 ,3263.8  ,604.4,607.9,611.2
XS GIS Cut Line= 2
     1848485.694      398640.048     1848927.284      398796.729
#Sta/Elev= 30
       0  996.28    29.9  994.62    79.8  993.15   109.7  991.87   129.6   990.6
   139.6  988.86   149.5  990.04   179.4  990.24   219.3  990.24   229.3  989.46
   238.4988.4409   239.6  988.33   249.2  988.17   255.8988.9282   269.2  990.42
   299.1   990.1     309  990.21     329  990.89     339  991.39   358.9  992.78
   368.9  994.54   378.8  997.03   398.8 1002.63   408.8  1005.7   418.7 1008.99
   428.7 1012.44   438.6 1016.14   448.6  1019.3   458.6 1019.92   468.6 1021.54
#Mann= 3 , 0 , 0
       0     .06       0   238.4    .045       0   255.8     .06       0
Bank Sta=238.4,255.8
XS Rating Curve= 0 ,0
Exp/Cntr=0.3,0.1

Type RM Length L Ch R = 1 ,2655.9  ,177.7,177.7,177.7
XS GIS Cut Line= 2
     1848258.888       399032.36     1848745.102       399307.45
#Sta/Elev= 30
       0     996    29.9  991.99    39.9  990.34    59.8   986.2    69.8  985.07
    99.8  984.24   129.7  984.85   159.6  983.52   199.5  983.49   239.4  981.78
   249.4  980.31   259.4  980.16   279.3  980.54   289.3  980.03   309.2  981.02
   329.2   980.6   349.2  980.68   369.1  980.06   379.1  979.54   384.7978.8951
     399  977.86     409  977.85   410.4  978.43     419  981.96     429  986.98
   458.9 1007.64   478.8 1023.23   488.8  1027.4   508.8 1032.03   558.6 1039.63
#Mann= 3 , 0 , 0
       0     .06       0   384.7    .045       0   410.4     .06       0
Bank Sta=384.7,410.4
XS Rating Curve= 0 ,0
Exp/Cntr=0.3,0.1

Type RM Length L Ch R = 1 ,2478.2  ,611.6,610.9,616.1
XS GIS Cut Line= 2
     1848172.382      399186.575     1848682.787      399475.352
#Sta/Elev= 30
       0  992.17    19.9   991.4    29.8   990.6    59.6  985.85    89.5  982.85
   119.3  980.74     159  980.06   208.7  980.82   228.6  980.08   248.5  979.82
   268.4  979.23   298.2  977.96   318.1  976.29     328  977.34     338  977.59
   367.8  977.21   379.2976.7119   397.6  974.72   405.8  974.85   407.5  974.88
   417.5  976.34   427.4  980.82   437.3  987.29   457.2   999.2   467.2 1006.54
   477.1 1014.39     487 1019.08   506.9 1023.52   556.6 1028.86   586.4 1033.64
#Mann= 3 , 0 , 0
       0     .06       0   379.2    .045       0   405.8     .06       0
Bank Sta=379.2,405.8
XS Rating Curve= 0 ,0
Exp/Cntr=0.3,0.1

Type RM Length L Ch R = 1 ,1867.3  ,77.3,75.9,68.7
XS GIS Cut Line= 4
     1847961.394        399554.7     1848087.148      399800.203
     1848163.247      399846.845     1848274.885      399950.162
#Sta/Elev= 30
       0  986.69    39.4  985.62    49.3  985.23    59.1  984.46      69  982.87
    88.7  978.81    98.5  977.32   118.2   975.6   137.9  971.77   147.8  970.44
   167.5  969.14   177.3   969.5   256.1  969.78   275.8  968.55   305.6  968.55
   335.3  967.35   345.3  967.46   356.6967.0418   365.1  966.81   374.6  967.23
   382.9968.3308   393.6  969.76   412.6  969.99   422.1  969.56   469.7  970.55
   479.2  970.54   488.7  971.34   498.2  972.67   507.7  974.74   517.2  975.56
#Mann= 3 , 0 , 0
       0     .06       0   356.6    .045       0   382.9     .06       0
#XS Ineff= 2 , 0
                          403.49          973.74
Permanent Ineff=
       F       F
Bank Sta=356.6,382.9
XS Rating Curve= 0 ,0
Exp/Cntr=0.3,0.1

Type RM Length L Ch R = 1 ,1791.4  ,472.5,483.4,494.2
XS GIS Cut Line= 4
     1847912.507      399595.846     1848041.483      399842.587
     1848126.842      399894.905      1848235.69       399995.64
#Sta/Elev= 30
       0  983.43    29.8  980.97    59.7  979.47    89.5  978.39    99.4   977.7
   119.3  975.81   129.3  974.44   139.2  972.48   149.2  970.88   159.1  969.68
     169  968.99   198.9  967.64   208.8  966.88   218.8  965.13   228.7  964.62
   238.6  966.34   248.6  967.24   296.6  967.58   305.7  967.43   314.8  966.44
   318.9966.2733   323.9  966.07   342.1  966.43   347.8967.7134   351.2  968.48
   369.4  974.92   398.3  977.52   437.9  980.18   477.4  982.12   526.8  982.38
#Mann= 3 , 0 , 0
       0     .06       0   318.9    .045       0   347.8     .06       0
Bank Sta=318.9,347.8
XS Rating Curve= 0 ,0
Exp/Cntr=0.3,0.1

Type RM Length L Ch R = 1 ,1308    ,533.9,552.8,571.3
XS GIS Cut Line= 2
     1847552.495      399899.137     1847817.512      400241.216
#Sta/Elev= 28
       0  982.83    29.5   980.7    49.2  979.62      59  978.86    68.8  978.61
    88.5  978.57   108.2  978.23     118  978.15   127.8  977.03   137.7  974.47
   147.5  966.62   157.4  956.73     159956.6282   167.2  956.12   175.2 957.115
     177  957.34   186.9  959.51   206.5  961.89   216.4  963.41   226.2  964.79
     236  966.37   245.9  969.28   265.5  975.29     295  983.94   304.9  985.11
   344.2  986.04   373.7  986.57   432.7  986.87
#Mann= 3 , 0 , 0
       0     .06       0     159    .045       0   175.2     .06       0
Bank Sta=159,175.2
XS Rating Curve= 0 ,0
Exp/Cntr=0.3,0.1

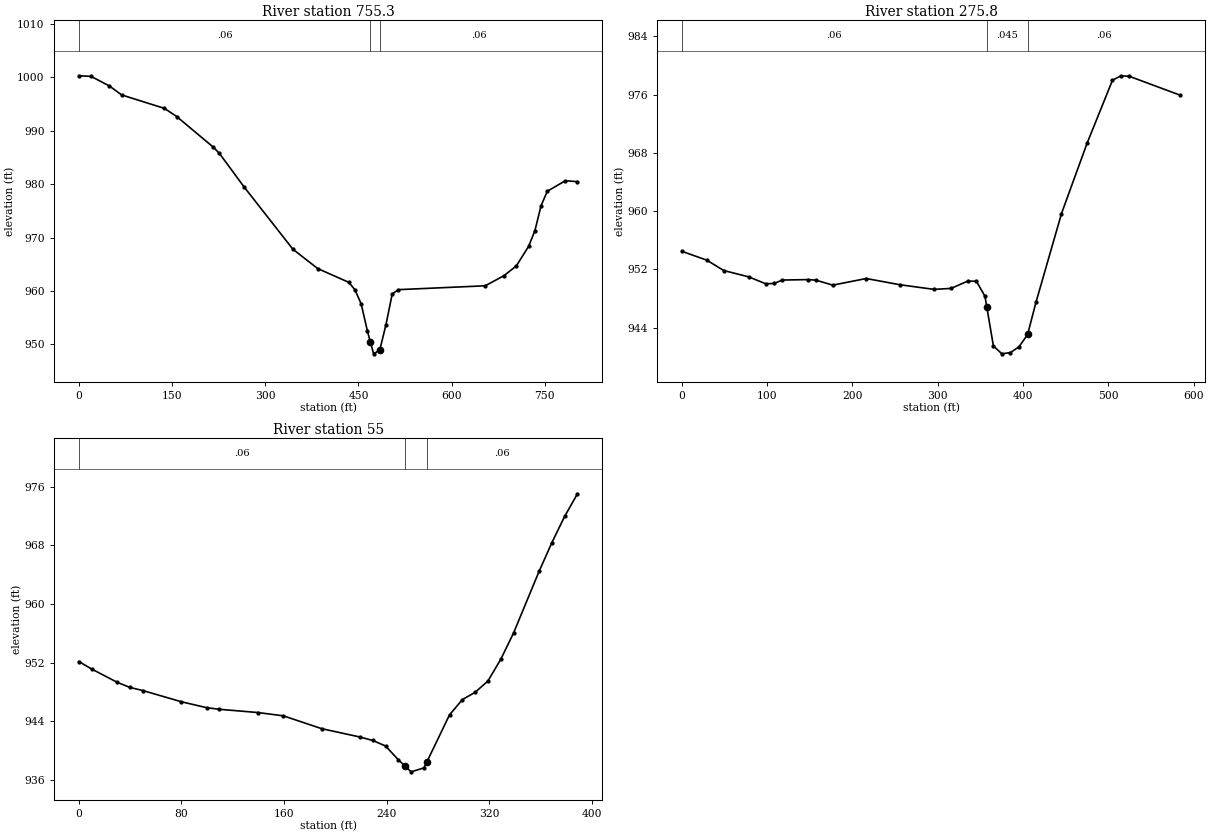
Type RM Length L Ch R = 1 ,755.3   ,470.1,479.5,486.7
XS GIS Cut Line= 4
     1847478.869      399985.978      1847466.65      400330.339
     1847413.896       400736.21     1847437.393      400778.696
#Sta/Elev= 30
       0 1000.27    19.7 1000.16    49.2  998.37    68.9  996.69   137.8  994.17
   157.5  992.65   216.6   986.9   226.4  985.73   265.8   979.5   344.6  967.81
   384.5   964.2   434.4  961.63   444.4  960.22   454.4  957.59   464.4  952.52
   469.2  950.47   474.4  948.25   484.3948.9576   494.3  953.72   504.3  959.44
   514.3  960.26     654  960.98     684  962.86     704  964.69   723.9  968.38
   733.9  971.28   743.9  975.98   753.9  978.67     783  980.64   802.4  980.46
#Mann= 3 , 0 , 0
       0     .06       0   469.2    .045       0   484.3     .06       0
Bank Sta=469.2,484.3
XS Rating Curve= 0 ,0
Exp/Cntr=0.3,0.1

Type RM Length L Ch R = 1 ,275.8   ,247.9,220.8,195.8
XS GIS Cut Line= 4
     1847144.628      400379.063     1847111.323      400592.664
     1847074.934      400716.641     1847032.768      400952.107
#Sta/Elev= 30
       0   954.5    29.5  953.27    49.1  951.86    78.6  950.98    98.3  950.04
   108.1  950.08   117.9  950.55   147.4  950.61   157.2  950.54   176.9  949.85
   216.2  950.76   255.9   949.9   295.7  949.27   315.6   949.4   335.4  950.41
   345.4  950.38   355.4  948.32   357.5946.8704   365.3  941.49   375.3  940.42
   385.3   940.6   395.2  941.37   405.4943.0801   415.2   947.5   445.1  959.67
     475   969.3   504.9  977.98   514.8  978.59   524.8  978.51   584.6  975.91
#Mann= 3 , 0 , 0
       0     .06       0   357.5    .045       0   405.4     .06       0
Bank Sta=357.5,405.4
XS Rating Curve= 0 ,0
Exp/Cntr=0.3,0.1

Type RM Length L Ch R = 1 ,55      ,54.3,55,55.6
XS GIS Cut Line= 2
     1846744.474      400663.086     1846971.786      400978.242
#Sta/Elev= 29
       0  952.17      10  951.15    29.9  949.34    39.8  948.64    49.8  948.22
    79.7   946.7    99.6  945.88   109.6  945.66   139.5  945.22   159.4  944.77
   189.3  943.02   219.2  941.88   229.2  941.41   239.1  940.65   249.1  938.77
   254.1  937.95     259  937.14     269  937.68   271.1938.4371   288.9   944.9
   298.9  946.98   308.9  947.98   318.8  949.51   328.8  952.46   338.8  956.05
   358.7  964.45   368.6  968.34   378.6  971.93   388.6  975.02
#Mann= 3 , 0 , 0
       0     .06       0   254.1    .045       0   271.1     .06       0
Bank Sta=254.1,271.1
XS Rating Curve= 0 ,0
Exp/Cntr=0.3,0.1

Chan Stop Cuts=-1
Use User Specified Reach Order=0
Composite Channel Slope=5